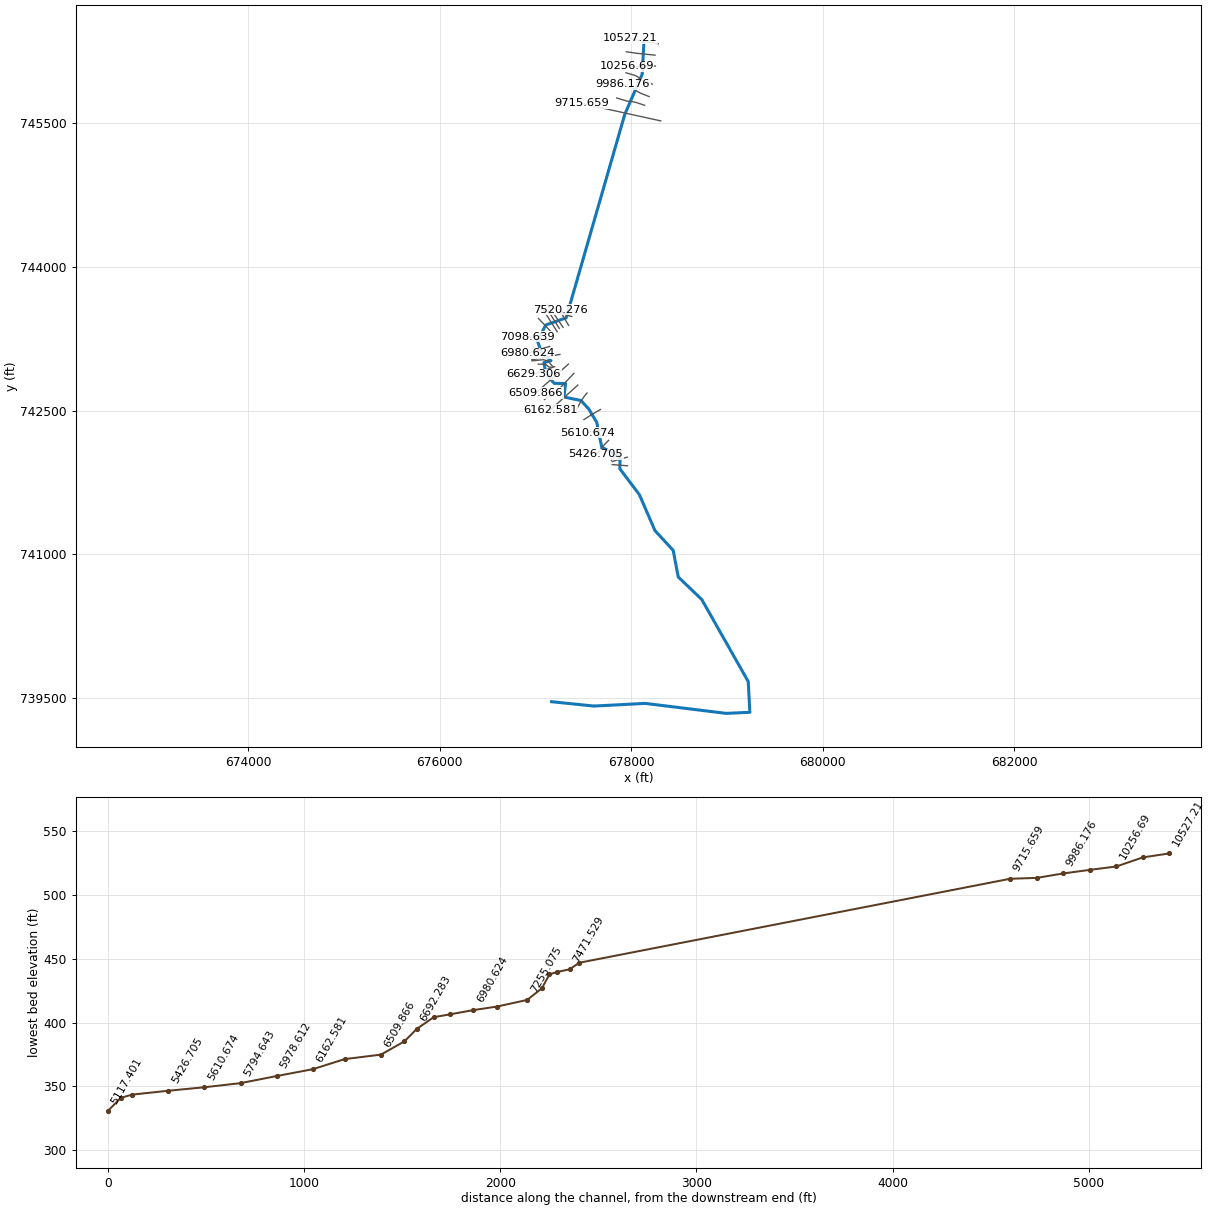
--- 4010_ras.prj (project) ---

Proj Title=4010
Current Plan=p01
Default Exp/Contr=0.3,0.1
English Units
Geom File=g01
Flow File=f01
Plan File=p01
Y Axis Title=Elevation
X Axis Title(PF)=Main Channel Distance
X Axis Title(XS)=Station
BEGIN DESCRIPTION:
RFD model 4010 exported to HEC-RAS
END DESCRIPTION:

--- 4010_ras.p01 (plan) ---

Plan Title=Plan 01
Program Version=4.10
Short Identifier=Plan 01
Geom File=g01
Flow File=f01
Subcritical Flow
Calc Critical at every XS
Secant Critical Depth

--- 4010_ras.f01 (steady flow) ---

Flow Title=Flow 01
Program Version=5.01
Number of Profiles= 6
Profile Names=10yr,25yr,50yr,100yr,100plus,500yr
River Rch & RM=4010,52,10527.21
   98.08  183.76  274.88  373.88  545.86 1206.42
River Rch & RM=4010,52,10391.95
  104.12  195.16  292.02  397.27  580.02 1271.46
River Rch & RM=4010,52,10256.69
  105.19  197.18  295.07  401.43  586.08 1282.94
River Rch & RM=4010,52,10121.44
  107.44  201.48  301.58  410.37  599.14 1308.05
River Rch & RM=4010,52,9986.176
  118.04  221.77  332.39  452.77  661.05 1426.51
River Rch & RM=4010,52,9850.918
  119.61  224.78  336.97  459.08  670.26 1444.05
River Rch & RM=4010,52,9715.659
  124.16  233.48  350.15  477.22  696.74 1494.02
River Rch & RM=4010,52,7520.276
  197.37  375.79  568.41  780.18 1139.07 2313.83
River Rch & RM=4010,52,7405.874
  203.09  386.98  585.64  804.19 1174.12 2377.11
River Rch & RM=4010,52,7368.441
  204.23   389.2  589.07  808.97  1181.1 2389.69
River Rch & RM=4010,52,7329.683
  204.88  390.48  591.03   811.7 1185.08 2396.86
River Rch & RM=4010,52,7098.639
  209.67   399.8  605.35  831.59 1214.13 2448.63
River Rch & RM=4010,52,6980.624
  210.31  401.07   607.3  834.31 1218.09 2455.74
River Rch & RM=4010,52,6860.184
  216.09  412.28  624.52  858.21 1252.98 2517.58
River Rch & RM=4010,52,6777.905
  223.13  426.24  646.19  888.61 1297.37 2597.97
River Rch & RM=4010,52,6692.283
  216.09  412.28  624.52  858.21 1252.98 2517.58
River Rch & RM=4010,52,6629.306
  223.13  426.24  646.19  888.61 1297.37 2597.97
River Rch & RM=4010,52,6509.866
  225.34  430.67   653.1  898.35  1311.6 2623.97
River Rch & RM=4010,52,6324.756
  227.35  434.63  659.23  906.94 1324.13 2646.42
River Rch & RM=4010,52,6162.581
  235.33  450.54  684.05  941.89 1375.16  2738.9
River Rch & RM=4010,52,5978.612
  236.64  453.17  688.15  947.67  1383.6 2754.19
River Rch & RM=4010,52,5794.643
  238.54  456.96  694.06  956.01 1395.77 2776.23
River Rch & RM=4010,52,5610.674
  239.26  458.41  696.34  959.21 1400.45 2784.68
River Rch & RM=4010,52,5426.705
  241.88  463.64   704.5  970.72 1417.26 2815.04
River Rch & RM=4010,52,5242.736
  263.65  506.86  771.72 1065.16 1555.13    3060
River Rch & RM=4010,52,5117.401
  266.75  513.08  781.44 1078.88 1575.17 3095.75
River Rch & RM=4010,52,4865.443
  268.16   515.9  785.86 1085.12 1584.27 3111.94
River Rch & RM=4010,52,4680.415
  273.19  525.99  801.65 1107.43 1616.85 3169.98
River Rch & RM=4010,52,4495.387
   275.7  531.02  809.53 1118.55 1633.09 3198.84
River Rch & RM=4010,52,4310.359
  278.16  535.97   817.3 1129.57 1649.17  3227.6
River Rch & RM=4010,52,4125.332
  286.58  553.11  844.37 1168.11 1705.44 3329.05
River Rch & RM=4010,52,3940.304
  287.89  555.79   848.6 1174.12 1714.22 3344.79
River Rch & RM=4010,52,3755.276
  289.08   558.2   852.4 1179.53 1722.11 3358.93
River Rch & RM=4010,52,3686.789
  290.14  560.35  855.79 1184.34 1729.14 3371.48
River Rch & RM=4010,52, 3500.09
  292.13  564.38  862.13 1193.35  1742.3 3394.97
River Rch & RM=4010,52,3272.821
  391.09   761.3 1169.01 1625.13 2372.69 4467.38
River Rch & RM=4010,52,3126.649
  392.46  764.07 1173.38 1631.33 2381.74 4482.81
River Rch & RM=4010,52,2938.198
  392.83  764.83 1174.57 1633.02 2384.21 4487.01
River Rch & RM=4010,52,2888.363
  393.45  766.08 1176.54 1635.83 2388.31 4494.02
River Rch & RM=4010,52,2766.566
  394.05  767.32  1178.5 1638.62 2392.39 4501.02
River Rch & RM=4010,52,2110.987
   394.3  767.81 1179.29 1639.74 2394.02 4503.82
River Rch & RM=4010,52,1478.813
  394.05  767.32  1178.5 1638.62 2392.39 4501.02
River Rch & RM=4010,52,544.9979
  392.46  764.07 1173.38 1631.33 2381.74 4482.81
Boundary for River Rch & Prof#=4010,52,1
Up Type= 0
Dn Type= 2
Boundary for River Rch & Prof#=4010,52,2
Up Type= 0
Dn Type= 2
Boundary for River Rch & Prof#=4010,52,2
Up Type= 0
Dn Type= 2
Boundary for River Rch & Prof#=4010,52,2
Up Type= 0
Dn Type= 2
Boundary for River Rch & Prof#=4010,52,2
Up Type= 0
Dn Type= 2
Boundary for River Rch & Prof#=4010,52,2
Up Type= 0
Dn Type= 2

--- 4010_ras.g01 (geometry) ---

Geom Title=4010
Program Version=4.10

River Reach=4010,52
Reach XY= 30
678133.082337171746357.514418259678113.637892723746012.375529364
677932.387892663745594.319973797677320.414513081 743469.22159417
677107.133263111743394.047983065677020.674929768743227.902149737
677060.258263111743114.360483065677161.299929768743021.131316409
677087.341596425743002.381316394677109.216596425742887.277149722
677195.154096395742785.193816379677313.904096395742783.631316394
677296.716596454 742642.48548305677474.841596395742606.027149722
677558.174929738742514.881316379677639.424929738742377.381316394
677690.987429708742119.568816394677883.174929738742014.881316409
677880.570763081741893.006316394678084.216596395741623.735483065
678247.758263052741247.346594185678437.862429768741040.749371946
678490.813818604740762.971594185678736.473540843740527.728538617
679221.687661231739670.726223797679238.456619829739350.125915885
678989.324675411739338.841193646678146.442730963739443.007860318
677609.116342068739415.230082527677168.633417547739460.665851012

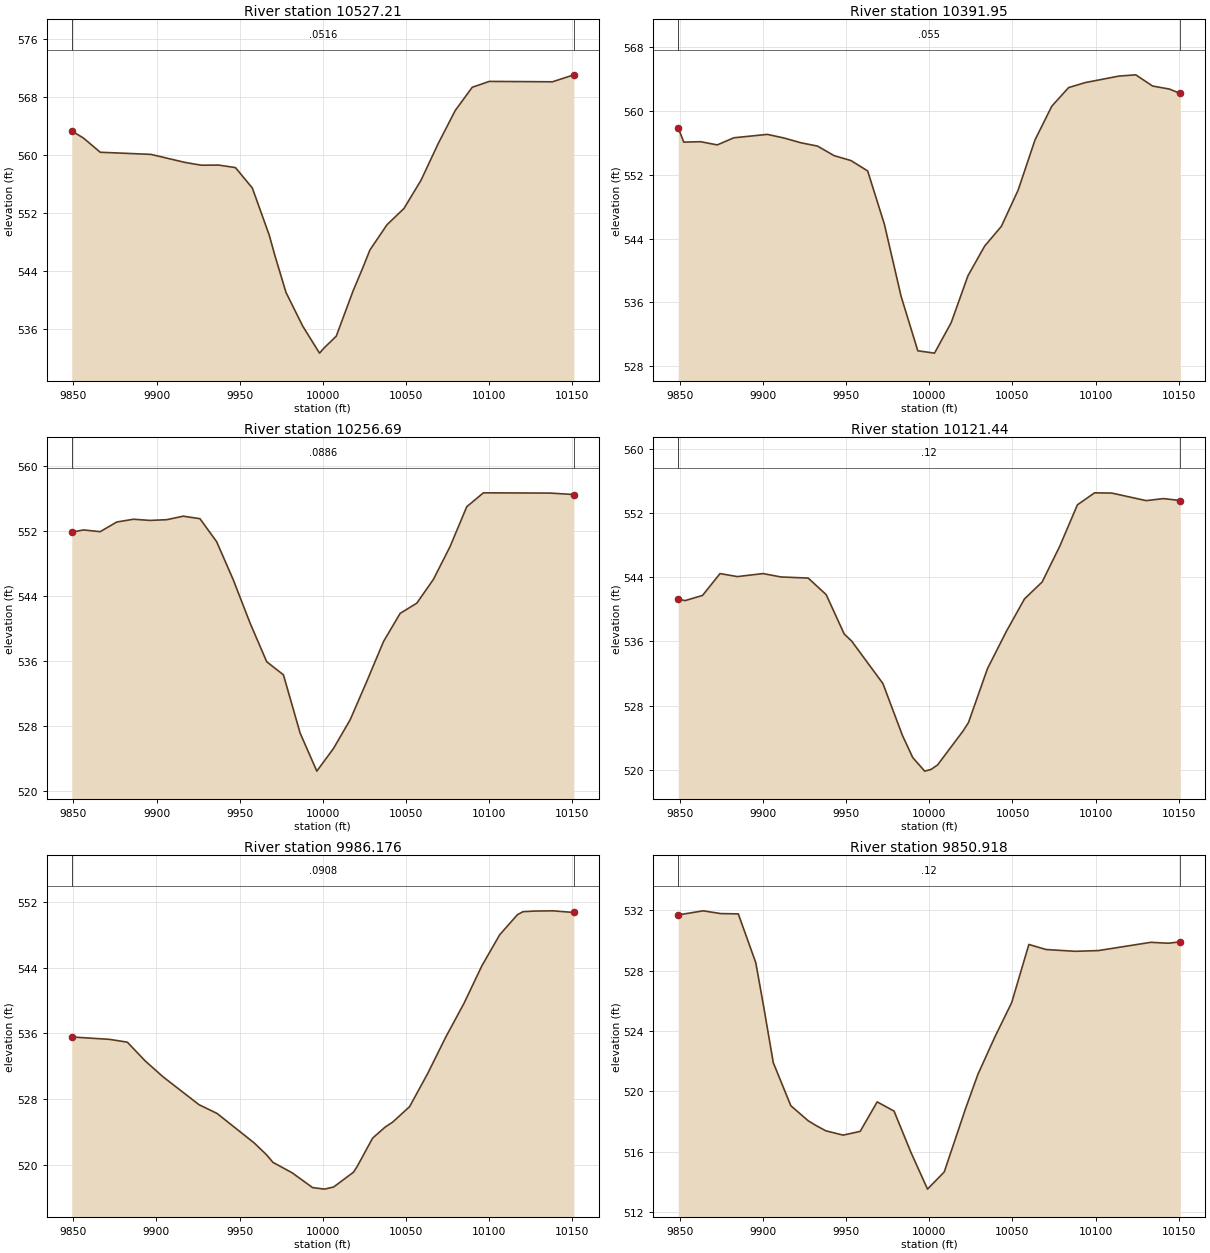
Type RM Length L Ch R = 1 ,10527.21,135.258800,135.258800,135.258800
XS GIS Cut Line= 6
678281.869788246746331.544078169678161.505583085746353.306827302
678134.015880202746356.452110672678132.020029584746356.580875229
678109.340976853746359.464249803 677985.43704625746387.871597125
#Sta/Elev= 29
9849.015563.35969855.996562.39479866.158 560.4279896.645560.13469916.969559.0351
9924.643558.72979927.131558.64279937.293558.65999947.456 558.3169957.618555.4972
 9967.78549.00789971.331546.07769977.879541.09659987.944536.45529998.009532.7385
   10001 533.50210008.08535.075710018.16541.291410023.86 544.39610028.32546.9504
10038.57 550.42710048.83552.685410059.09556.578610069.35561.597210079.61566.1687
10089.87569.383910100.13570.195210138.13570.140210150.98571.1009
#Mann= 3 , 0 , 0
9849.015  0.0516       09849.015  0.0516       010150.98  0.0516       0
#XS Ineff= 2 , 0
       0                               0
Bank Sta=9849.015,10150.98
Exp/Cntr=0.3,0.1

Type RM Length L Ch R = 1 ,10391.95,135.258800,135.258800,135.258800
XS GIS Cut Line= 5
678248.326797836 746212.24608752678099.136895556746227.719589006
 678097.13855945746227.801153745678060.469250924746231.284809084
677948.487654012746247.478291621
#Sta/Elev= 30
 9849.01557.86699852.354556.09349862.408556.14949872.462555.74589882.515556.6404
9902.623557.06539912.676  556.61 9922.73556.01589932.784555.59589942.837554.3925
9952.891553.78249962.945552.47829972.998545.79549983.052536.74999993.105529.9175
10003.15529.625210013.19533.455410023.24539.320810033.28543.047610043.36 545.532
10053.46550.081310063.57556.360710073.67560.596310083.78562.933310093.88 563.567
10114.09564.378910124.19564.5367 10134.3563.1305 10144.4562.750810150.98562.2005
#Mann= 3 , 0 , 0
 9849.01   0.055       0 9849.01   0.055       010150.98   0.055       0
#XS Ineff= 2 , 0
       0                               0
Bank Sta=9849.01,10150.98
Exp/Cntr=0.3,0.1

Type RM Length L Ch R = 1 ,10256.69,135.258800,135.258800,135.258800
XS GIS Cut Line= 6
678252.060368442 746098.87121266678180.246783418746099.719372641
678077.628311632746090.715261663678041.208948024746089.216031351
 677995.49912915746091.447612087677950.961702959746096.971192674
#Sta/Elev= 28
9849.044551.87729856.105552.15439866.106551.94219876.106553.12819886.107553.4717
9896.108553.32649906.109553.41489916.109553.8484 9926.13553.53779936.168 550.708
9946.207546.00229956.245540.71099966.284535.93589976.322534.3338 9986.36527.1721
9996.399522.483610006.44 525.27310016.48528.809310026.51533.549510036.51538.4247
10046.52541.893410056.53543.144510066.54546.080510076.55550.113510086.57555.0115
10096.58556.720710136.82556.689210150.97556.5102
#Mann= 3 , 0 , 0
9849.044  0.0886       09849.044  0.0886       010150.97  0.0886       0
#XS Ineff= 2 , 0
       0                               0
Bank Sta=9849.044,10150.97
Exp/Cntr=0.3,0.1

Type RM Length L Ch R = 1 ,10121.44,135.258700,135.258700,135.258700
XS GIS Cut Line= 6
678218.936869887745909.586328603678122.885750236 745943.86267215
678095.353906884745960.590672359678066.624235225745985.922140447
678041.963617261 745999.46780296677945.179632116746028.192224351
#Sta/Elev= 30
  9849.1541.2931 9853.23541.10129863.721541.75119874.212544.47299884.704   544.1
9900.073544.47719910.901 544.051  9927.2543.91829938.045 541.844 9948.89536.9243
9953.373536.04349972.111530.75699983.871524.27299990.047521.51339997.232519.8185
   10001520.024510004.98520.5902 10020.3524.827210023.56525.886710034.97532.6097
10046.38537.281110057.23541.315510067.84543.427710078.45547.902410089.02 553.057
10099.36554.554810109.71554.522810130.39553.580910140.73553.833810150.88553.5939
#Mann= 3 , 0 , 0
  9849.1    0.12       0  9849.1    0.12       010150.88    0.12       0
#XS Ineff= 2 , 0
       0                               0
Bank Sta=9849.1,10150.88
Exp/Cntr=0.3,0.1

Type RM Length L Ch R = 1 ,9986.176,135.258800,135.258800,135.258800
XS GIS Cut Line= 6
678186.390415199745779.991436744678098.966332808745814.267228926
678068.464624352 745830.23934877678038.979775847745851.625423339
678018.388262899745863.233397325677913.312768747745905.834945407
#Sta/Elev= 30
 9849.05535.57599871.839 535.2829882.493  534.949893.148 532.6639903.877530.7233
 9925.58  527.319936.431526.24249958.743522.64459966.114521.21169970.031520.2759
9981.635518.99099993.833517.1975   10001517.006610006.54517.268610018.48519.0749
10020.78519.806710029.96523.231510037.55524.586810041.95525.174410052.17 527.064
10063.08531.1141   10074535.580810084.92539.681410095.69544.271510106.38548.0467
10117.08550.506910120.42550.867310127.77550.943810138.47550.969810150.97550.7676
#Mann= 3 , 0 , 0
 9849.05  0.0908       0 9849.05  0.0908       010150.97  0.0908       0
#XS Ineff= 2 , 0
       0                               0
Bank Sta=9849.05,10150.97
Exp/Cntr=0.3,0.1

Type RM Length L Ch R = 1 ,9850.918,135.258800,135.258800,135.258800
XS GIS Cut Line= 6
 678139.29147133745688.897401565678048.103286379745719.006287972
678019.960923762745724.963084161677972.292009955745730.143273364
677944.530087163745735.264990022677848.191932387745765.315094181
#Sta/Elev= 29
9849.047531.69969864.097531.97089874.628531.78819885.159531.7682 9895.69528.5307
9900.405525.63399906.221521.89989916.752519.05199927.283518.04499932.299517.7132
9937.814517.38569948.249517.09989958.471517.34959968.692519.30529978.837518.6926
9988.903515.97839998.969  513.5210009.02514.661510021.79518.844610029.21521.1176
10039.38523.590410049.55525.880310059.91529.740710070.28 529.40510087.74529.2876
10101.62 529.33410133.25529.8834 10143.8529.821610150.98529.9176
#Mann= 3 , 0 , 0
9849.047    0.12       09849.047    0.12       010150.98    0.12       0
#XS Ineff= 2 , 0
       0                               0
Bank Sta=9849.047,10150.98
Exp/Cntr=0.3,0.1

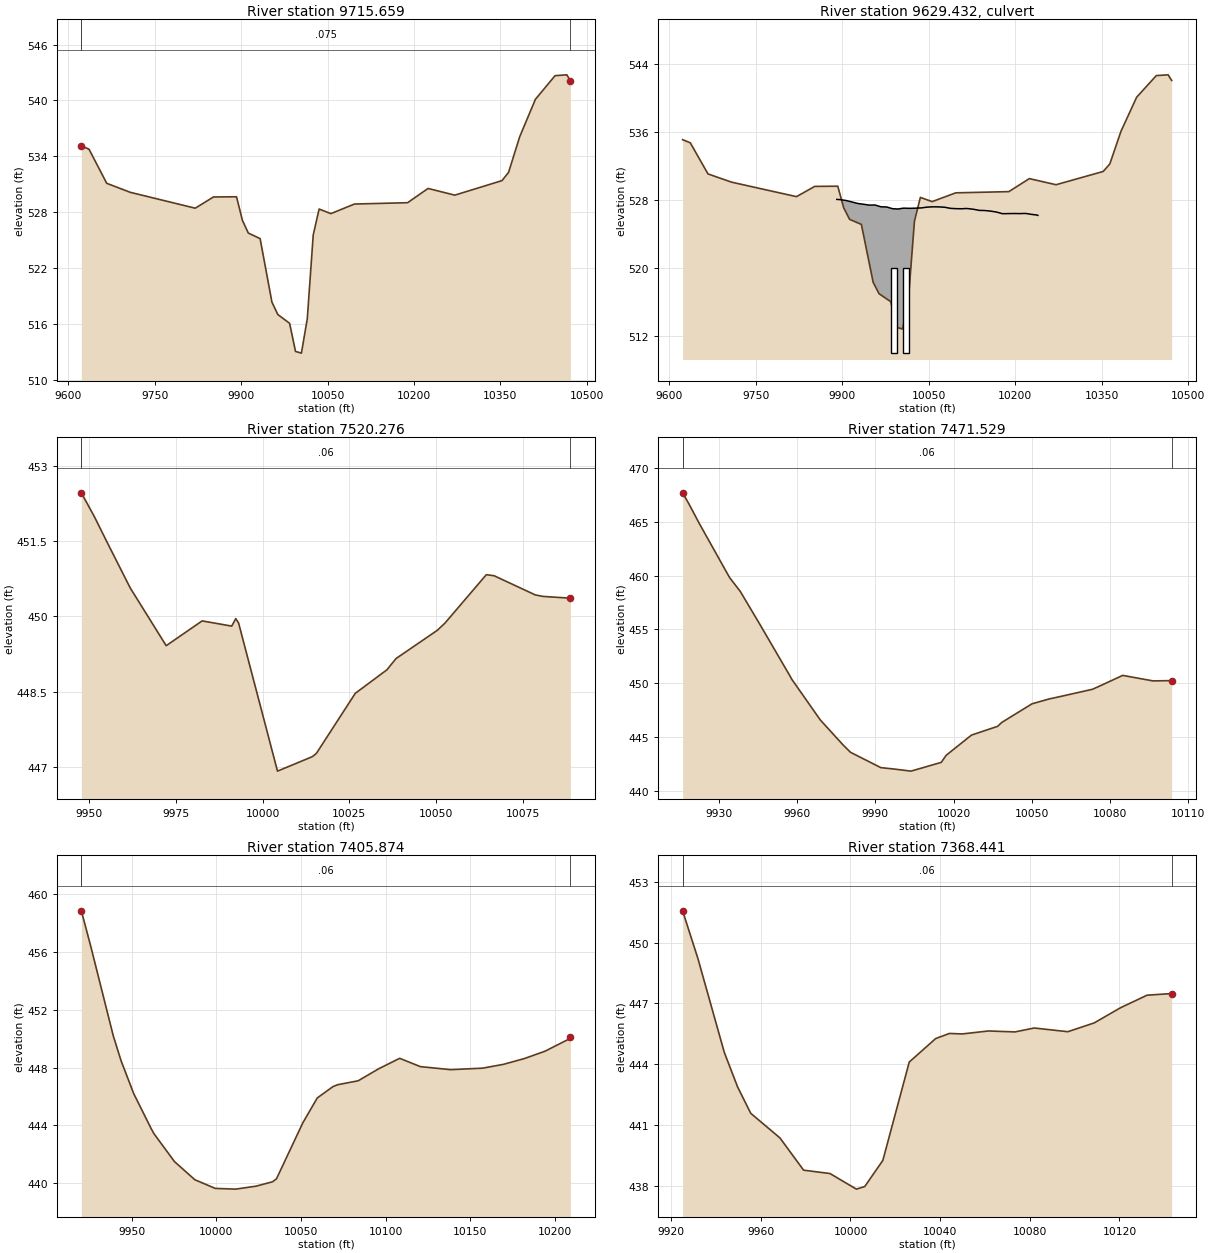
Type RM Length L Ch R = 1 ,9715.659,2195.382800,2195.382800,2195.382800
XS GIS Cut Line= 2
678308.011755109745525.755527228677479.018699586745708.047193885
#Sta/Elev= 30
9622.781535.12329636.104534.75219666.821531.08969707.776530.11989820.404528.4158
9852.077529.62059892.077529.64349902.316527.11169912.555525.74349933.032 525.146
 9953.51518.32659963.749516.98819984.227516.04329994.466513.0208 10004.7512.8368
10014.94516.540410025.18525.523710035.42528.3253 10055.9  527.8310096.86528.8631
10189.01 529.00510224.58530.537710270.92529.818110352.83531.379910364.27532.2628
10383.54536.091110410.83540.115810444.98542.661510465.46 542.75110471.58542.0916
#Mann= 3 , 0 , 0
9622.781   0.075       09622.781   0.075       010471.58   0.075       0
#XS Ineff= 2 , 0
       0                               0
Bank Sta=9622.781,10471.58
Exp/Cntr=0.3,0.1

Type RM Length L Ch R = 2 ,9629.432,,,
Bridge Culvert--1,0,-1,-1, 0
Deck Dist Width WeirC Skew NumUp NumDn MinLoCord MaxHiCord MaxSubmerge Is_Ogee
27.691,2140,2.6,0,41,41, , , 0.95, 0, 0,0,,
 9890.36 9895.17 9896.59 9906.63 9916.68 9926.72 9936.76 9946.80 9956.84 9966.89
 9976.93 9986.97 9997.0110004.6710007.0510017.1010027.1410037.1810047.2210057.26
10067.3110077.3510087.3910097.4310107.4710114.1810117.5210127.5610137.6010147.64
10157.6810167.7310177.7710187.8110197.8510207.8910217.9410223.6910227.9810238.02
10239.41
  528.09  528.07  528.06  527.96  527.79  527.61  527.52  527.42  527.43  527.22
  527.20  527.00  526.96  527.05  527.06  527.04  527.06  527.09  527.18  527.22
  527.21  527.17  527.04  527.00  526.99  527.02  527.01  526.93  526.80  526.78
  526.71  526.60  526.41  526.42  526.43  526.42  526.44  526.38  526.33  526.25
  526.21
                                                                                
                                                                                
                                                                                
                                                                                
        
 9890.36 9895.17 9896.59 9906.63 9916.68 9926.72 9936.76 9946.80 9956.84 9966.89
 9976.93 9986.97 9997.0110004.6710007.0510017.1010027.1410037.1810047.2210057.26
10067.3110077.3510087.3910097.4310107.4710114.1810117.5210127.5610137.6010147.64
10157.6810167.7310177.7710187.8110197.8510207.8910217.9410223.6910227.9810238.02
10239.41
  528.09  528.07  528.06  527.96  527.79  527.61  527.52  527.42  527.43  527.22
  527.20  527.00  526.96  527.05  527.06  527.04  527.06  527.09  527.18  527.22
  527.21  527.17  527.04  527.00  526.99  527.02  527.01  526.93  526.80  526.78
  526.71  526.60  526.41  526.42  526.43  526.42  526.44  526.38  526.33  526.25
  526.21
                                                                                
                                                                                
                                                                                
                                                                                
        
BR Coef=-1 , 0 , 0 ,, 0 ,,,0.8,-1,,0,
WSPro=,,,, 1 ,,,, 0 ,,,, 0 ,,,,-1 ,-1 ,-1 , 0 , 0 , 0 , 0 , 0
Multiple Barrel Culv=2,10,10,2140,0.013,0.7,1,8,3,510,442,2,Culvert #1, 0, 27.691
 9990.00 9990.0010010.0010010.00
Culvert Bottom n=0.013
BC Design=,, 0 ,, 0 ,,,,,,

Type RM Length L Ch R = 1 ,7520.276,48.747400,48.747400,48.747400
XS GIS Cut Line= 4
677378.602983832 743483.06265378677336.768034995743494.472185284
677296.834674746 743514.75579685677259.436765939743552.153705657
#Sta/Elev= 23
9947.743452.45619951.478451.98419955.106451.48049961.843450.56139972.208449.4121
9982.574449.90599991.106449.80239992.272449.95069993.089 449.86410004.31446.9146
10014.35447.202510015.52447.267410026.74448.4636 10035.9 448.93410036.24448.9642
10038.49449.156110050.38449.717610052.63449.863510064.53450.826110066.77450.8053
10078.67450.422910080.92450.393310088.78450.3583
#Mann= 3 , 0 , 0
9947.743    0.06       09947.743    0.06       010088.78    0.06       0
#XS Ineff= 2 , 0
       0                               0
Bank Sta=9947.743,10088.78
Exp/Cntr=0.3,0.1

Type RM Length L Ch R = 1 ,7471.529,65.654600,65.654600,65.654600
XS GIS Cut Line= 2
677346.206199557743389.470805004677251.193314105743551.182787105
#Sta/Elev= 28
9916.092467.69459918.474466.68079922.505464.83759934.104459.81289938.214458.5197
9945.702455.4659  9957.3 450.6429957.954450.35259968.899446.56559977.695444.2236
9980.497443.55369992.095442.13039997.435441.991210003.69441.803610015.29442.6183
10017.18443.278210026.89445.156910036.92445.973110038.49446.332310050.09448.0648
10056.66448.516710061.69448.784110073.28449.4172 10076.4449.756810084.88 450.709
10096.14 450.21310096.48450.197810103.65450.2223
#Mann= 3 , 0 , 0
9916.092    0.06       09916.092    0.06       010103.65    0.06       0
#XS Ineff= 2 , 0
       0                               0
Bank Sta=9916.092,10103.65
Exp/Cntr=0.3,0.1

Type RM Length L Ch R = 1 ,7405.874,37.433000,37.433000,37.433000
XS GIS Cut Line= 3
677288.103068173743369.368072495677197.879224867743503.336809576
677124.059716672743607.230932206
#Sta/Elev= 29
9920.251458.86359925.806456.40199939.098450.20119943.708448.47129951.154446.1988
 9961.61443.7375 9963.21443.40279975.267441.47769987.323440.21779999.379439.6174
10011.44439.567410023.49439.773510033.22440.076410035.55440.283910051.12444.1658
10059.66445.891710069.02446.682110071.72446.807910083.81447.078510096.08447.9216
10108.34448.636410120.61  448.0610138.53447.850110157.41447.955310169.68448.2192
10181.95448.617610194.21449.129510207.59449.924510209.22450.1027
#Mann= 3 , 0 , 0
9920.251    0.06       09920.251    0.06       010209.22    0.06       0
#XS Ineff= 2 , 0
       0                               0
Bank Sta=9920.251,10209.22
Exp/Cntr=0.3,0.1

Type RM Length L Ch R = 1 ,7368.441,38.758000,38.758000,38.758000
XS GIS Cut Line= 2
677247.974031746743359.216724351677132.578013748743544.307367146
#Sta/Elev= 23
 9925.14451.57979931.955449.2259 9943.74444.58139949.663442.87729955.524441.5741
9968.565440.35539979.093438.76369990.877438.595910002.66 437.82610006.37437.9537
10014.45439.246310026.23444.106710038.01445.267210044.17445.5201 10049.8445.4956
10061.58445.642610073.37445.594610081.97445.788710096.94 445.60610108.72446.0402
 10120.5446.792410132.29447.410310143.26447.4912
#Mann= 3 , 0 , 0
 9925.14    0.06       0 9925.14    0.06       010143.26    0.06       0
#XS Ineff= 2 , 0
       0                               0
Bank Sta=9925.14,10143.26
Exp/Cntr=0.3,0.1

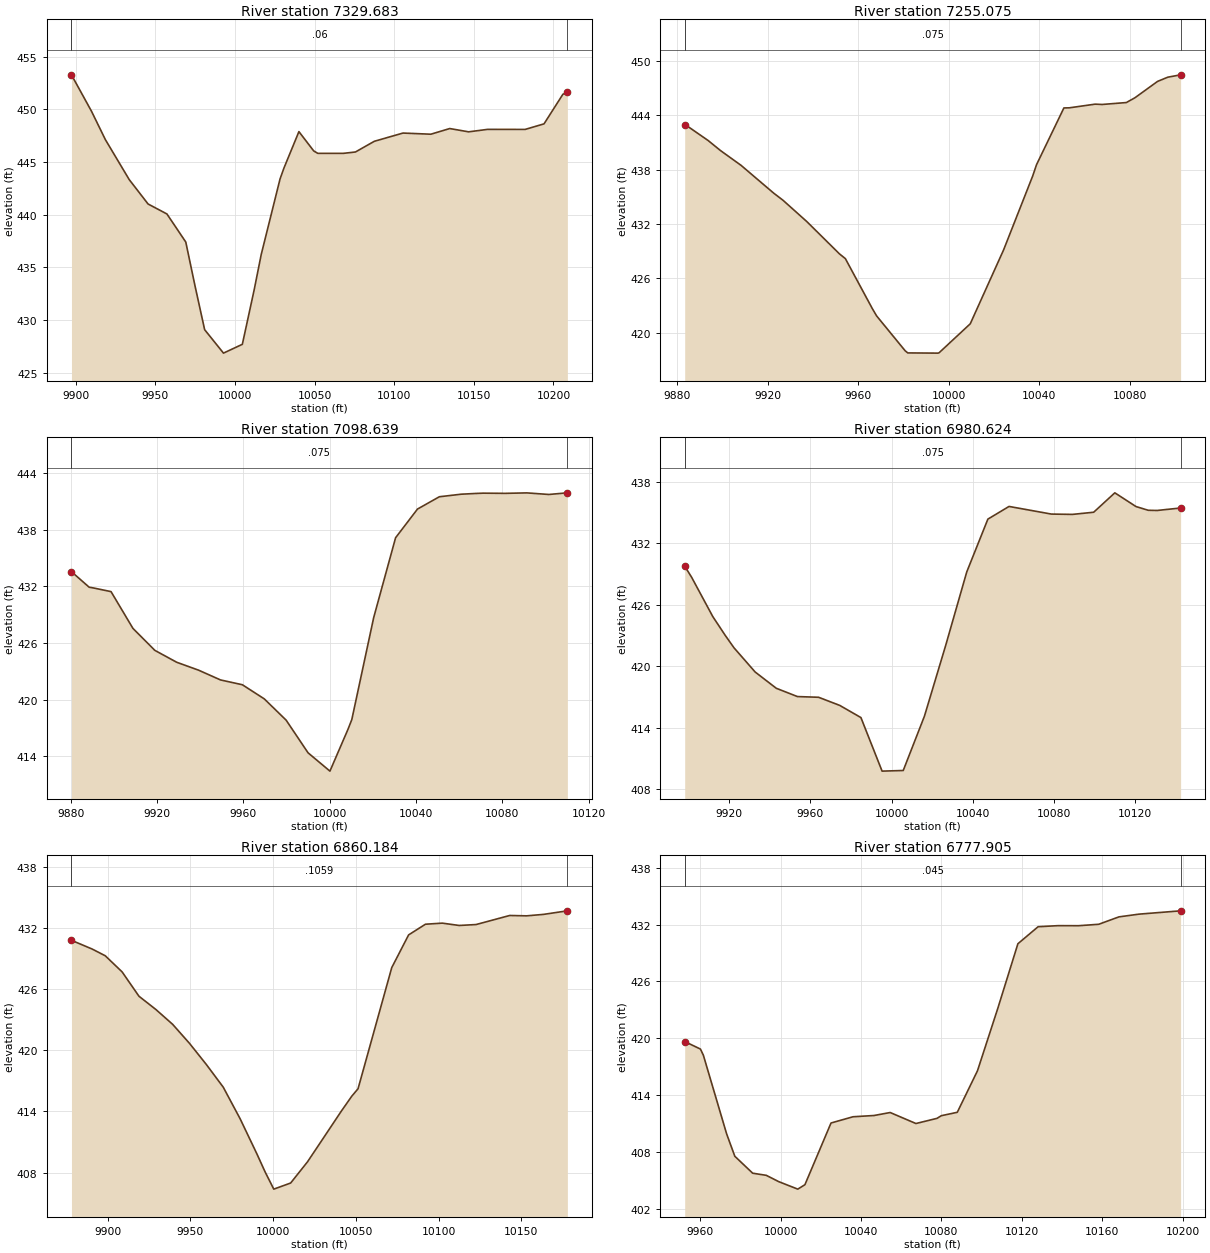
Type RM Length L Ch R = 1 ,7329.683,74.608300,74.608300,74.608300
XS GIS Cut Line= 2
  677226.4145329743324.366638333677059.747866243743587.387471661
#Sta/Elev= 30
9897.365453.27079909.954449.81059918.691447.10959933.631443.32439945.469441.0085
9957.308440.06089969.147437.39659974.739433.37719980.985429.07599992.824426.8497
10004.66427.6878 10012.1432.8658 10016.5436.202410028.34443.387710030.79444.4216
10040.18447.878510049.47446.047310052.02 445.81610068.15445.816310075.69445.9453
10087.53446.960710105.52447.741310123.05447.633410134.89448.170810146.73447.8588
10158.56448.090310182.24448.088810194.08448.614610205.92 451.42110208.75451.6155
#Mann= 3 , 0 , 0
9897.365    0.06       09897.365    0.06       010208.75    0.06       0
#XS Ineff= 2 , 0
       0                               0
Bank Sta=9897.365,10208.75
Exp/Cntr=0.3,0.1

Type RM Length L Ch R = 1 ,7255.075,156.436300,156.436300,156.436300
XS GIS Cut Line= 2
677182.143699586743303.533305004 677031.10203287743462.387471676
#Sta/Elev= 29
9883.245442.96669885.269442.67889893.612441.23399899.068440.12529908.125438.4977
9922.637435.40899926.665434.6401 9937.15432.29539951.662428.70659954.263428.1852
9966.175422.66389968.061421.85939980.687418.0025 9981.86417.7662  9995.2 417.743
9995.659417.777410009.46420.981910024.22  429.1610037.06437.315510038.74438.5544
10050.85444.833310053.25444.846610064.65445.251510067.76445.217610078.45445.4292
10082.27445.962310092.25447.766110096.79448.232310102.44448.4925
#Mann= 3 , 0 , 0
9883.245   0.075       09883.245   0.075       010102.44   0.075       0
#XS Ineff= 2 , 0
       0                               0
Bank Sta=9883.245,10102.44
Exp/Cntr=0.3,0.1

Type RM Length L Ch R = 1 ,7098.639,118.014800,118.014800,118.014800
XS GIS Cut Line= 2
677143.081199557743233.220805004676916.518699616743272.283305004
#Sta/Elev= 28
9880.264433.54039888.464431.90079890.735431.80699898.612431.43199908.759427.5436
9918.907425.21819929.054 423.9589939.202423.11969949.349422.08889949.591422.0763
9959.497421.57829969.644420.08539979.792417.83119989.939414.378410000.09412.4385
10008.45416.857810010.23417.890410020.38428.689510030.53437.133810040.68 440.167
10050.82441.470210060.97  441.74 10067.3441.813810071.12441.849510081.27  441.83
10091.41441.878510101.56441.711510110.17441.8855
#Mann= 3 , 0 , 0
9880.264   0.075       09880.264   0.075       010110.17   0.075       0
#XS Ineff= 2 , 0
       0                               0
Bank Sta=9880.264,10110.17
Exp/Cntr=0.3,0.1

Type RM Length L Ch R = 1 ,6980.624,120.440200,120.440200,120.440200
XS GIS Cut Line= 2
  677148.2895329743170.720805004  676913.9145329743100.408305019
#Sta/Elev= 26
9897.944429.77919901.379428.68049911.819 424.8459917.853423.03989922.259421.8021
  9932.7419.4374 9943.14417.8465 9953.58417.0369 9964.02 416.9689974.461 416.173
9984.901414.98539995.341409.756210005.78409.817110016.22415.112410026.66421.9915
 10037.1429.197710047.54434.365510057.98435.603510078.86434.8577 10089.3434.8266
10099.74435.037510110.18 436.93310120.63435.591610126.66435.229310131.07435.2099
10142.64435.4532
#Mann= 3 , 0 , 0
9897.944   0.075       09897.944   0.075       010142.64   0.075       0
#XS Ineff= 2 , 0
       0                               0
Bank Sta=9897.944,10142.64
Exp/Cntr=0.3,0.1

Type RM Length L Ch R = 1 ,6860.184,82.278300,82.278300,82.278300
XS GIS Cut Line= 2
677255.060366213743087.387471676  676960.7895329743030.095805019
#Sta/Elev= 29
 9878.04430.77369890.533429.91839898.477429.25759908.665427.67569918.852 425.289
 9929.04423.99469939.228422.53289949.416420.66639959.604418.59219969.791416.3763
9979.979413.28349990.167409.82459995.189 408.03610000.35406.377710010.54 406.975
10020.73409.053110041.11 414.00710047.52415.494210051.29416.218810071.67428.0971
10081.86431.302410092.04432.351210102.23 432.45610112.42432.227810122.61432.3172
10142.98433.207310153.17 433.17210163.36433.313410177.84433.6638
#Mann= 3 , 0 , 0
 9878.04  0.1059       0 9878.04  0.1059       010177.84  0.1059       0
#XS Ineff= 2 , 0
       0                               0
Bank Sta=9878.04,10177.84
Exp/Cntr=0.3,0.1

Type RM Length L Ch R = 1 ,6777.905,85.621800,85.621800,85.621800
XS GIS Cut Line= 4
677180.922501653 742958.97051473677132.340432227 743017.52925919
677082.890825748 743032.27738744676964.472031385743020.131870046
#Sta/Elev= 28
 9952.32419.67229960.155418.87859961.596418.24199973.148 409.9679977.258407.5853
9986.142 405.8019992.919 405.5759999.135 404.90810008.58404.122410012.13404.5875
10025.12411.089310036.07411.7465 10046.5411.878810054.55412.192810067.37411.0345
10077.81411.576810080.01411.859210087.94412.216410097.99416.592910108.05423.1375
 10118.1429.977210128.15431.7692 10138.2 431.88210148.26431.875710158.31432.0267
10168.36432.806810178.41433.095610199.05 433.444
#Mann= 3 , 0 , 0
 9952.32   0.045       0 9952.32   0.045       010199.05   0.045       0
#XS Ineff= 2 , 0
       0                               0
Bank Sta=9952.32,10199.05
Exp/Cntr=0.3,0.1

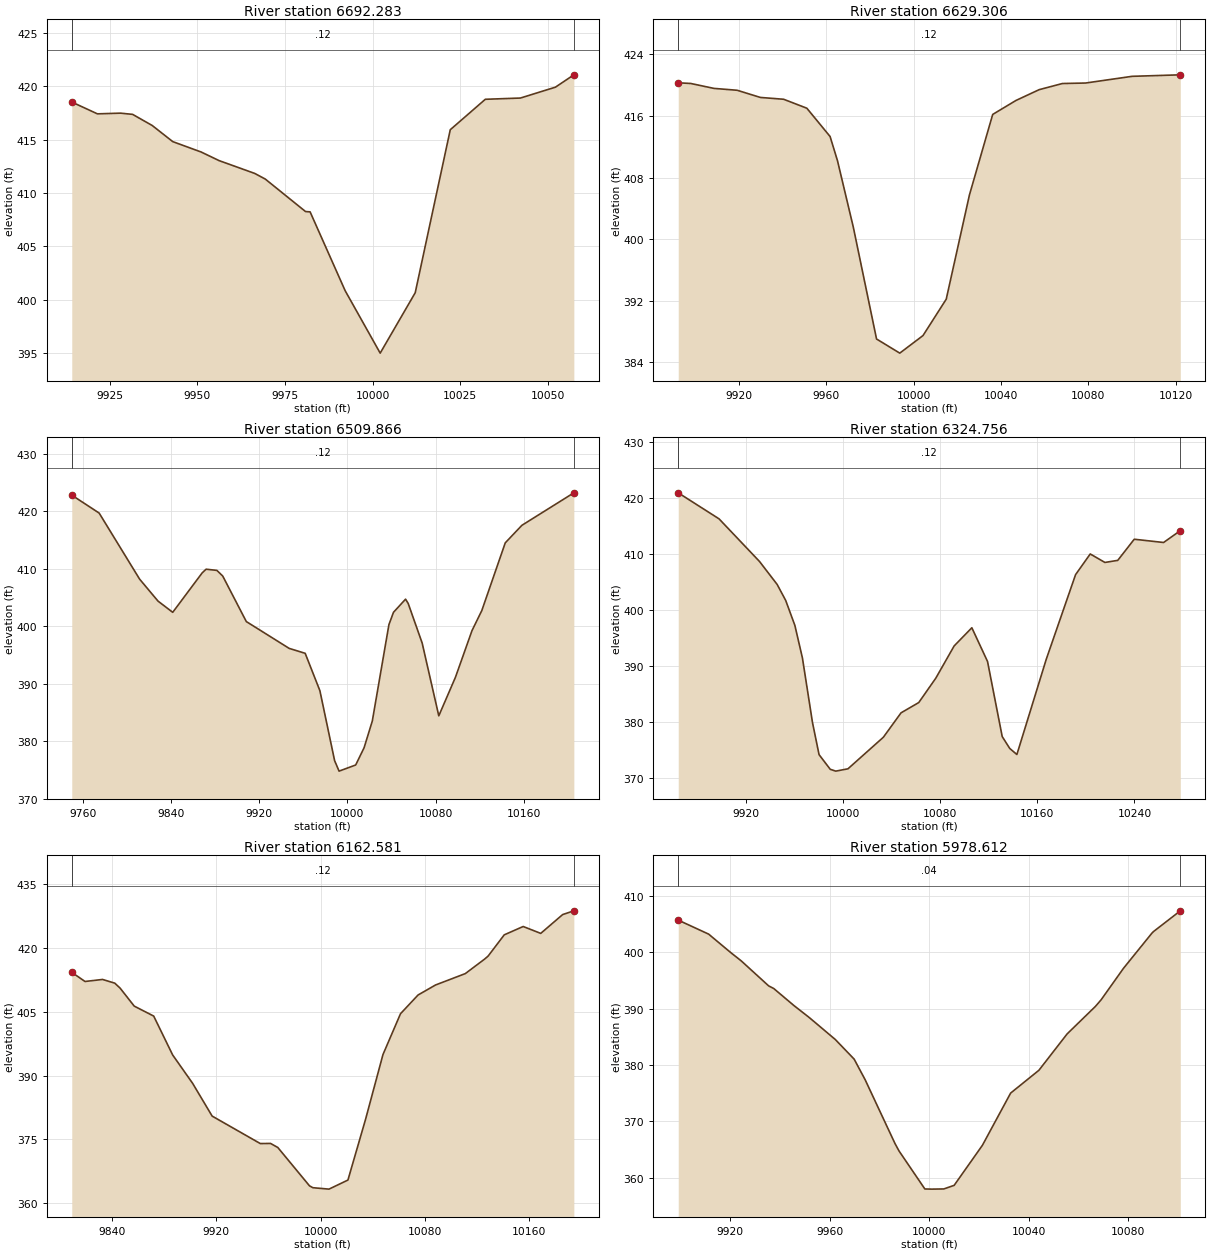
Type RM Length L Ch R = 1 ,6692.283,62.977400,62.977400,62.977400
XS GIS Cut Line= 4
677162.283919394742953.616858944677139.433222741742955.901928604
677106.299712598742984.465299398677029.749878854742985.607834235
#Sta/Elev= 21
9914.148418.52379921.468417.41489928.049417.47999931.518417.36589937.113416.3205
9942.966414.81069951.047413.83899956.169413.03229966.362411.82719969.372411.2979
9980.859408.25159982.159408.2238 9992.16400.831110002.16394.975310012.16400.6413
10016.69407.576410022.16415.927410032.16418.780410042.17418.896710052.17419.9171
10057.42421.0745
#Mann= 3 , 0 , 0
9914.148    0.12       09914.148    0.12       010057.42    0.12       0
#XS Ineff= 2 , 0
       0                               0
Bank Sta=9914.148,10057.42
Exp/Cntr=0.3,0.1

Type RM Length L Ch R = 1 ,6629.306,119.440400,119.440400,119.440400
XS GIS Cut Line= 2
677200.372866243742959.783305019 676984.22703287742881.658305019
#Sta/Elev= 22
9892.292420.30049898.005 420.2159908.638419.57639919.272419.33279929.905418.4013
9940.538418.16599951.171417.00099961.804413.32869965.201410.17829972.437 401.559
9983.071387.03969993.704385.205510004.34387.486210014.97392.2078 10025.6 405.753
10036.24416.194810046.87418.0058 10057.5419.411110068.14420.208410078.77420.2729
10100.04 421.14210122.12421.3374
#Mann= 3 , 0 , 0
9892.292    0.12       09892.292    0.12       010122.12    0.12       0
#XS Ineff= 2 , 0
       0                               0
Bank Sta=9892.292,10122.12
Exp/Cntr=0.3,0.1

Type RM Length L Ch R = 1 ,6509.866,185.109500,185.109500,185.109500
XS GIS Cut Line= 2
 677343.60203287742985.824971676677002.456199557742683.741638333
#Sta/Elev= 30
9749.807422.82299774.654419.70419811.389408.20299828.082404.38259841.439402.4305
9868.153409.29119871.726409.93379881.511409.7265 9886.81408.74579908.225400.8212
9947.147396.15089961.653395.2963 9975.01388.78569988.367376.6136  9992.4374.7938
10007.48375.862210015.08378.848810022.57383.514210037.65400.284610041.79402.4333
10052.74404.717910055.15403.967410067.82397.084310082.91384.419310097.99391.1089
10113.07 399.25610121.94402.733910143.24414.520210158.33417.570910205.48423.2249
#Mann= 3 , 0 , 0
9749.807    0.12       09749.807    0.12       010205.48    0.12       0
#XS Ineff= 2 , 0
       0                 10051.8       0
Bank Sta=9749.807,10205.48
Exp/Cntr=0.3,0.1

Type RM Length L Ch R = 1 ,6324.756,162.174700,162.174700,162.174700
XS GIS Cut Line= 3
677400.893699586742889.470805019677231.622866243742709.783305019
 677093.60203287742616.033305019
#Sta/Elev= 30
9864.052420.87619897.671416.23929930.983408.64929945.566404.54399952.624401.6792
 9960.15397.25159966.363391.45979974.734379.85629980.101374.19989989.318371.5865
 9993.84 371.262 10003.9371.675210033.07377.302810047.65381.653110062.24383.4866
10076.27387.8287 10091.4393.577610105.99396.822110118.92390.805610131.01377.4198
10137.22375.3053 10143.1374.224310167.27391.181410191.45406.286310203.54409.9765
10215.63408.464610226.21408.835610239.81412.603310263.98412.021310277.76414.1328
#Mann= 3 , 0 , 0
9864.052    0.12       09864.052    0.12       010277.76    0.12       0
#XS Ineff= 2 , 0
       0                10102.46       0
Bank Sta=9864.052,10277.76
Exp/Cntr=0.3,0.1

Type RM Length L Ch R = 1 ,6162.581,183.969000,183.969000,183.969000
XS GIS Cut Line= 2
677442.560366243742767.074971661 677156.10203287742509.262471661
#Sta/Elev= 30
 9809.01414.18999819.181412.04519832.635412.52099842.009411.65419846.089 410.496
9856.957406.27069871.906403.93269886.449394.82129901.803388.15529916.751380.4874
9953.718374.04159961.596374.06889967.171373.12019991.493364.12549994.078363.6909
10006.44363.357410020.99365.482610034.44379.633710047.89394.915710061.35404.4845
 10074.8408.870410088.25411.225210111.08413.891510126.03417.320410128.61418.0081
10140.98422.980710155.52424.936410168.98423.321110185.82427.7345 10194.4428.6124
#Mann= 3 , 0 , 0
 9809.01    0.12       0 9809.01    0.12       0 10194.4    0.12       0
#XS Ineff= 2 , 0
       0                               0
Bank Sta=9809.01,10194.4
Exp/Cntr=0.3,0.1

Type RM Length L Ch R = 1 ,5978.612,183.969000,183.969000,183.969000
XS GIS Cut Line= 6
677538.500075022742684.328519935677508.402627347742648.789345677
677478.807201162742604.362279779677477.625459279 742602.74874759
677475.704789108742599.943270189677429.860875454742514.938261689
#Sta/Elev= 27
9899.047405.69199911.271403.21239919.936400.01989924.375398.46729935.409394.0335
9937.479393.55619945.618390.52899951.755388.41389962.187384.53469969.793381.0452
9974.202377.40339986.218366.0808 9987.83364.76989998.234358.0153   10001357.9865
10005.88358.019710010.02358.657610021.38365.756110032.74375.0181 10044.1379.0592
10055.46385.512510066.82390.381710069.09391.537910078.19397.183710089.55403.3737
10090.15403.647210100.98407.3408
#Mann= 3 , 0 , 0
9899.047    0.04       09899.047    0.04       010100.98    0.04       0
#XS Ineff= 2 , 0
       0                               0
Bank Sta=9899.047,10100.98
Exp/Cntr=0.3,0.1

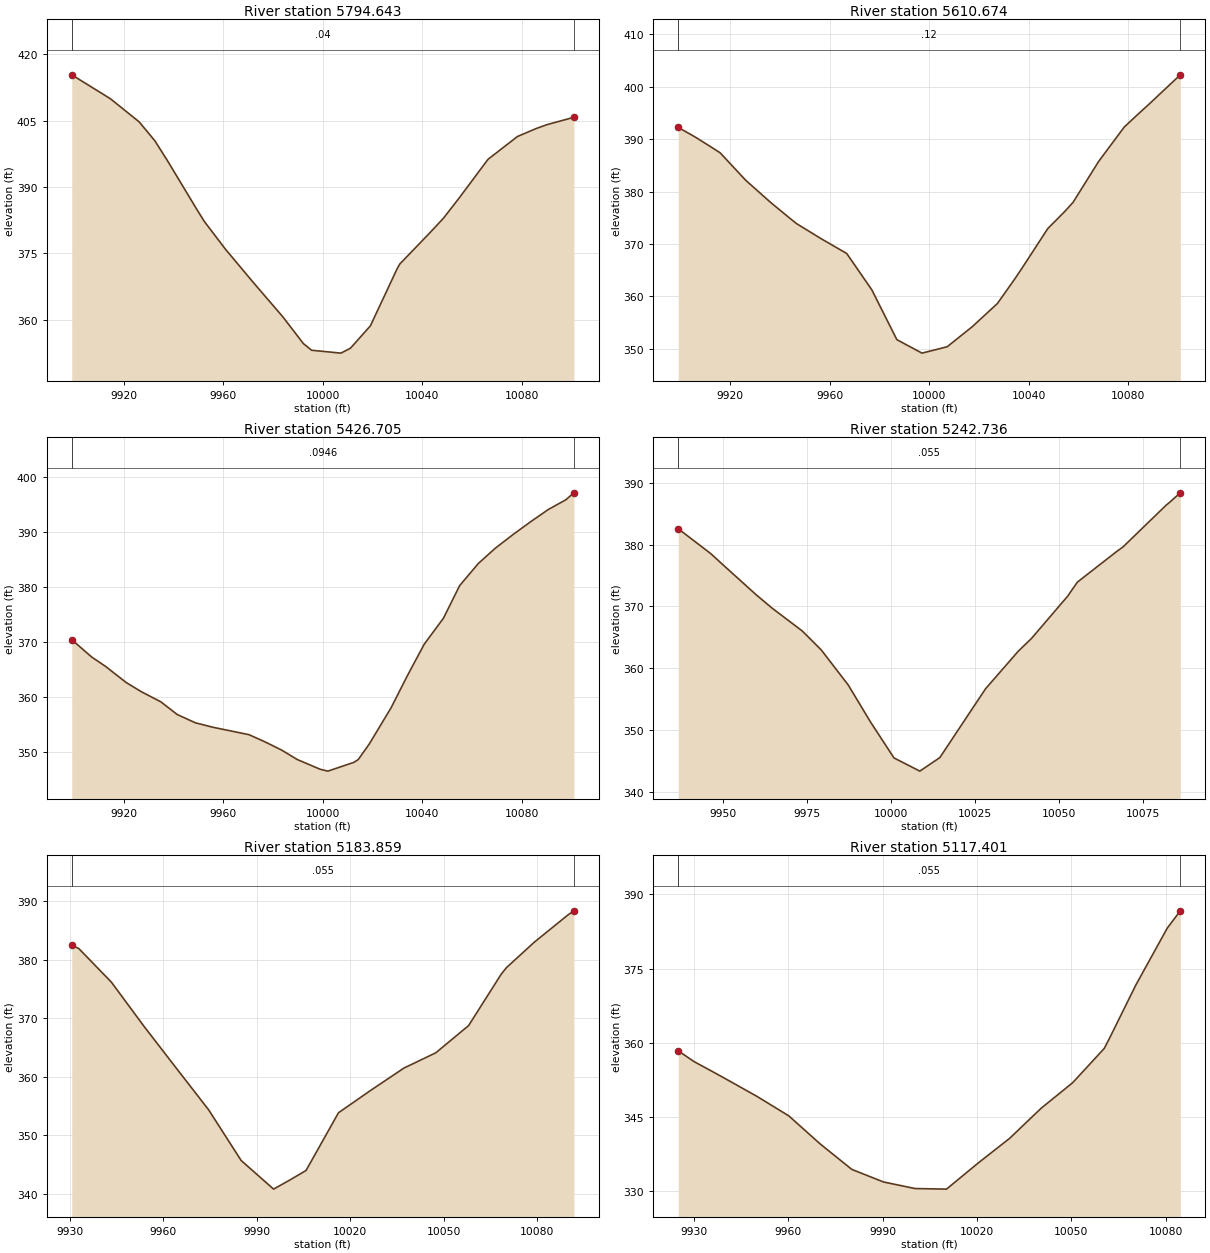
Type RM Length L Ch R = 1 ,5794.643,183.969100,183.969100,183.969100
XS GIS Cut Line= 5
677678.444243581742511.784108279677598.262115096742465.253432373
677592.037826851742461.460224702677590.331892885742460.416294962
677505.837652859742406.937677382
#Sta/Elev= 25
9899.006415.3623 9914.55409.95389926.111404.72639932.445400.44159937.673395.7868
9949.235384.99859952.369382.17179960.797375.94659972.292368.22699983.921360.6238
9992.198354.56449995.531353.057910007.31352.410810011.13353.524610019.14358.5768
10029.83371.408910030.98372.572810042.81379.470810048.52382.914410054.65387.3404
10066.48396.256310078.32401.410910085.92 403.22910090.15404.0841   10101405.7507
#Mann= 3 , 0 , 0
9899.006    0.04       09899.006    0.04       0   10101    0.04       0
#XS Ineff= 2 , 0
       0                               0
Bank Sta=9899.006,10101
Exp/Cntr=0.3,0.1

Type RM Length L Ch R = 1 ,5610.674,183.969000,183.969000,183.969000
XS GIS Cut Line= 6
677741.449947031742307.755045923677696.520245793742297.705373364
677643.080246829742290.478383688 677641.12575746742290.054153438
 677588.28983726742281.953377258677543.122513702742270.838572579
#Sta/Elev= 30
9899.034392.24439905.643 390.4719911.655388.6892 9915.89387.40149926.137 382.181
9936.384377.85979945.074374.47489946.608373.89879956.699370.96279965.261368.6204
 9966.79368.20299976.881361.27549986.972351.75869997.063349.1897    9999349.4219
   10001349.6576 10007.2350.403710017.31354.239910027.43358.667810034.35363.3101
10037.55365.575610047.66372.942810054.45  376.1910057.84377.954710068.14385.7672
10078.44392.327610083.55 394.58510088.74396.834210099.03401.416510100.97402.2769
#Mann= 3 , 0 , 0
9899.034    0.12       09899.034    0.12       010100.97    0.12       0
#XS Ineff= 2 , 0
       0                               0
Bank Sta=9899.034,10100.97
Exp/Cntr=0.3,0.1

Type RM Length L Ch R = 1 ,5426.705,183.969000,183.969000,183.969000
XS GIS Cut Line= 6
677764.439012178742190.778486182677705.899801944742130.043621967
677696.503170567742117.603428975677689.038444228742106.331270799
677671.013313492742085.511098244677627.646554772742042.758801523
#Sta/Elev= 30
9899.056370.39939907.082 367.2349912.657365.5292 9920.97362.58469927.067360.9072
9934.859 359.0789941.477356.75729948.748355.24869955.887354.42889970.297353.0882
9976.526351.8254 9983.41 350.2819989.731348.5567    9999346.769210002.04346.4374
10012.53348.042710014.29348.5614 10018.7351.388510027.51358.021610033.97363.7971
10040.79369.577910048.51374.309810055.04 380.26310062.55384.294110069.28387.0463
10076.59389.602210083.52391.885410090.64394.124310097.77 395.91910100.96397.1796
#Mann= 3 , 0 , 0
9899.056  0.0946       09899.056  0.0946       010100.96  0.0946       0
#XS Ineff= 2 , 0
       0                               0
Bank Sta=9899.056,10100.96
Exp/Cntr=0.3,0.1

Type RM Length L Ch R = 1 ,5242.736,58.877300,58.877300,58.877300
XS GIS Cut Line= 2
677902.096427888742084.039255708677792.511717319741982.132454827
#Sta/Elev= 23
 9936.53 382.5499946.221378.53239949.804 376.7569959.877371.83419964.489369.7405
9973.533 366.0329979.173362.97529987.188 357.3399993.858 351.34210000.84345.5559
10008.54343.4249 10014.5345.606510023.23 352.72710028.16356.734910037.91362.8003
10041.81364.8303 10052.6371.661710055.47373.914610067.28378.900910069.12379.6221
10081.97386.356310082.78386.710610086.18388.3425
#Mann= 3 , 0 , 0
 9936.53   0.055       0 9936.53   0.055       010086.18   0.055       0
#XS Ineff= 2 , 0
       0                               0
Bank Sta=9936.53,10086.18
Exp/Cntr=0.3,0.1

Type RM Length L Ch R = 1 ,5183.859,66.457900,66.457900,66.457900
XS GIS Cut Line= 3
677957.237779051742014.240077034  677844.8611013741982.132454827
677802.981594115741968.172619089
#Sta/Elev= 23
9930.697382.55139933.024381.89179943.425376.17569953.825368.67159964.225361.4958
9964.332 361.4279974.625354.35759985.025345.72679995.425340.836110000.73342.4191
10005.83344.020210016.23353.877110026.63357.727410037.03361.439110037.13 361.491
10047.43364.112510047.57364.174810057.97368.769910068.51377.617510070.13378.6798
10079.05383.021510089.59387.567810091.72388.3712
#Mann= 3 , 0 , 0
9930.697   0.055       09930.697   0.055       010091.72   0.055       0
#XS Ineff= 2 , 0
       0                               0
Bank Sta=9930.697,10091.72
Exp/Cntr=0.3,0.1

Type RM Length L Ch R = 1 ,5117.401,66.930600,66.930600,66.930600
XS GIS Cut Line= 2
677960.029746175 741924.19913651 677800.88761881741936.762988687
#Sta/Elev= 20
9924.996358.35239930.041356.16999935.172354.39999940.073352.68729950.104349.1044
9960.135345.19799970.166339.48669980.197334.34949990.228331.813810000.26330.4802
10010.29330.359910020.32335.622710030.35340.630610040.38  346.7310050.41351.9042
10060.45 358.84210062.23 361.03910070.48 371.66110080.51383.221710084.63386.6924
#Mann= 3 , 0 , 0
9924.996   0.055       09924.996   0.055       010084.63   0.055       0
#XS Ineff= 2 , 0
       0                               0
Bank Sta=9924.996,10084.63
Exp/Cntr=0.3,0.1