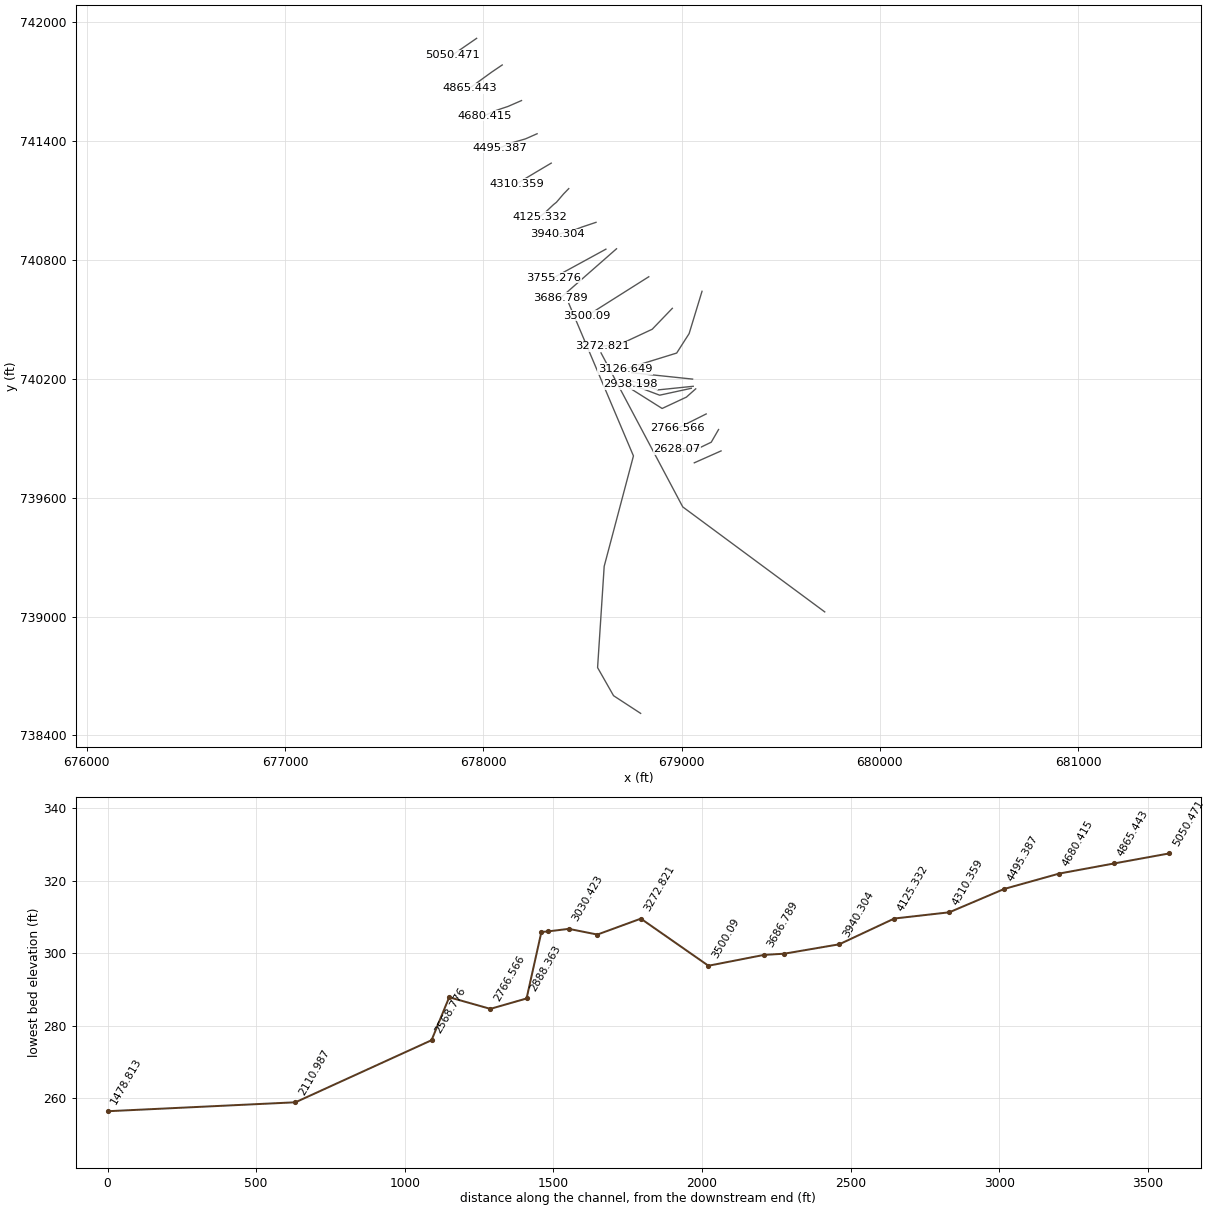
HEC-RAS study 4010_ras.prj: 4010

--- 4010_ras.g01 (geometry) --- (continued)

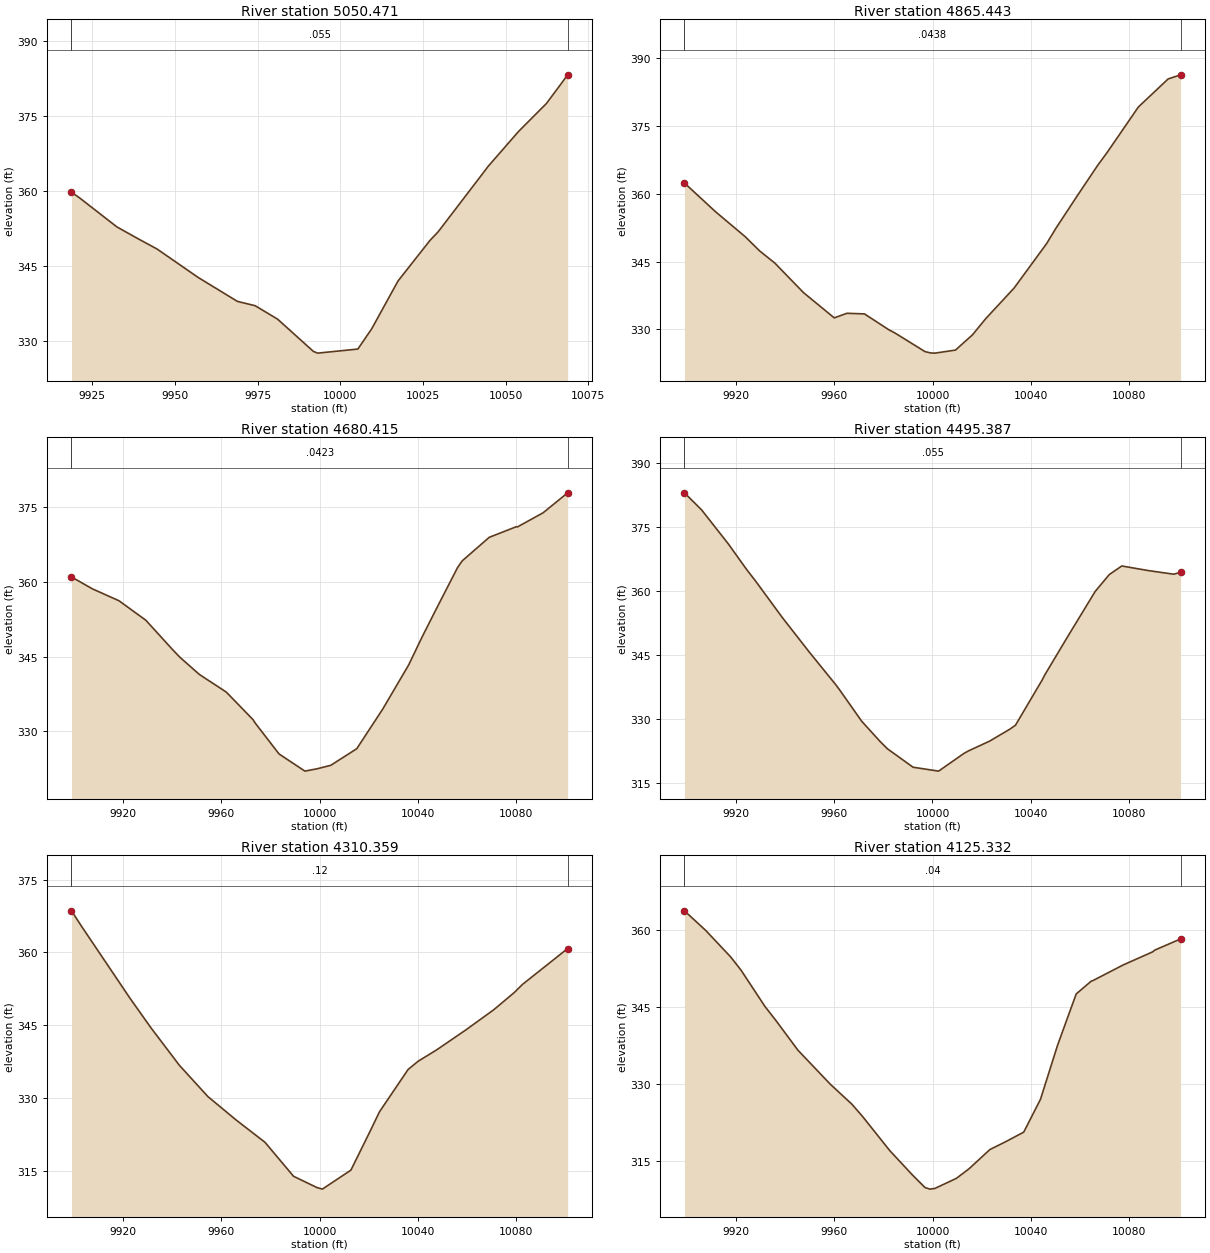
Type RM Length L Ch R = 1 ,5050.471,185.027700,185.027700,185.027700
XS GIS Cut Line= 2
 677966.31167224741916.521226868677842.767125994741831.366228864
#Sta/Elev= 24
9918.723359.67859920.316358.96199921.404358.44349932.462352.75799939.025350.3339
9944.607348.34059956.645342.83489956.752342.77169968.898337.87319974.266 337.007
9981.043334.32869991.887 327.8699993.188327.530510005.33328.344910009.51332.3875
10017.48341.953910027.13350.052910029.62 351.78610041.77362.288710044.75364.8798
10053.91371.823710062.37377.439910066.06380.711810068.77383.1553
#Mann= 3 , 0 , 0
9918.723   0.055       09918.723   0.055       010068.77   0.055       0
#XS Ineff= 2 , 0
       0                               0
Bank Sta=9918.723,10068.77
Exp/Cntr=0.3,0.1

Type RM Length L Ch R = 1 ,4865.443,185.027800,185.027800,185.027800
XS GIS Cut Line= 5
678095.501466678741782.163349337678043.211349332741746.754030584
678013.360594866 741725.16082863678011.747007965741723.979161455
677930.905593607 741665.12279643
#Sta/Elev= 28
9899.007362.30759899.612362.09589911.689356.03149923.767350.51369929.617347.3805
9935.844 344.6699947.452 338.1669959.998332.56389965.151333.58119972.292 333.443
9982.213329.94499984.635329.24229996.977325.09669999.272324.8036   10001324.7673
10009.35325.439910016.26328.806510021.72 332.42310033.25339.184210046.45348.9902
10050.24352.381910058.82359.479710067.23366.289310071.19369.224310083.56379.0112
10084.22379.421310095.93385.4118   10101386.3223
#Mann= 3 , 0 , 0
9899.007  0.0438       09899.007  0.0438       0   10101  0.0438       0
#XS Ineff= 2 , 0
       0                               0
Bank Sta=9899.007,10101
Exp/Cntr=0.3,0.1

Type RM Length L Ch R = 1 ,4680.415,185.027700,185.027700,185.027700
XS GIS Cut Line= 6
678192.754307796 741602.64359134 678124.16042129741572.749147729
678100.291110056741564.822634372678098.362877996741564.291671921
678060.092739764741551.040302992678005.897989292741526.569536695
#Sta/Elev= 26
9899.024361.00379907.483358.62319918.391356.20579929.299352.29489940.208346.3761
9943.185344.84119951.116341.38529962.025337.86099972.933332.30719973.849331.5998
9983.501325.42119994.038321.9681    9999322.441210004.56323.135310015.14326.4777
10025.72334.451310036.31343.3587 10041.5348.706310047.09354.173810056.18362.9078
10058.06364.238510069.03 368.959   10080 371.08610080.48 371.04210090.98373.9007
10100.96 377.909
#Mann= 3 , 0 , 0
9899.024  0.0423       09899.024  0.0423       010100.96  0.0423       0
#XS Ineff= 2 , 0
       0                               0
Bank Sta=9899.024,10100.96
Exp/Cntr=0.3,0.1

Type RM Length L Ch R = 1 ,4495.387,185.027800,185.027800,185.027800
XS GIS Cut Line= 6
678271.398066335741435.242347831678213.649080651741409.708211291
678178.382525013741399.197005942678176.427283109741398.776257685
678147.168399704741390.439699557678082.883054126741363.938625973
#Sta/Elev= 28
9899.058382.92599906.054 378.9269916.988 370.9099924.386364.95229927.922362.3263
9938.855 353.7379949.789 345.6769960.723 337.915  9962.2336.77059971.225329.3936
9978.684324.6724 9981.66322.96289992.095318.640110002.48317.727310012.88321.9099
10014.78322.504110023.28324.766110031.42327.537210033.77328.490510044.59339.0414
 10045.7340.2705 10055.4349.614410066.22359.835710071.93363.774310077.03365.7889
10087.85364.709610098.17363.861610100.96364.3122
#Mann= 3 , 0 , 0
9899.058   0.055       09899.058   0.055       010100.96   0.055       0
#XS Ineff= 2 , 0
       0                               0
Bank Sta=9899.058,10100.96
Exp/Cntr=0.3,0.1

Type RM Length L Ch R = 1 ,4310.359,185.027700,185.027700,185.027700
XS GIS Cut Line= 4
678342.770086763741287.086363114678256.747321656741236.145909458
 678255.10414543741235.005746361678169.194334167741183.882769997
#Sta/Elev= 22
9899.026368.5697 9903.12365.39169922.746350.6454  9931.3344.53699942.922336.7826
9954.543330.33199966.165325.45549977.787320.91649989.409313.9168    9999311.5813
10001.12311.270910012.76315.182610020.57323.190410024.39327.194110036.03335.9018
10040.12337.600610047.67 339.94410059.68344.100210070.94348.220710079.23351.7404
10082.58 353.41610100.97360.8021
#Mann= 3 , 0 , 0
9899.026    0.12       09899.026    0.12       010100.97    0.12       0
#XS Ineff= 2 , 0
       0                               0
Bank Sta=9899.026,10100.97
Exp/Cntr=0.3,0.1

Type RM Length L Ch R = 1 ,4125.332,185.027800,185.027800,185.027800
XS GIS Cut Line= 6
 678431.03788573741158.493359308678404.670302557  741131.3571773
678369.058255222741089.640156185678353.603586268741077.288108332
678314.523317014741040.301646741678286.929886736741017.715003273
#Sta/Elev= 29
9899.034363.80419907.698359.98529917.848354.82399922.048352.25779931.791 345.176
9936.397 342.3469945.229336.63779958.377330.01799967.167326.12269971.525323.7259
9982.569317.0852 9991.72312.37239996.995309.85029998.986 309.554   10001 309.696
10009.72311.653310014.84313.509510023.36317.270710029.39318.700610037.13320.6636
10043.94327.054310050.89337.580610058.48347.595310064.66350.116110065.32 350.213
10077.63353.258810089.48355.780810090.55356.164410100.98358.3278
#Mann= 3 , 0 , 0
9899.034    0.04       09899.034    0.04       010100.98    0.04       0
#XS Ineff= 2 , 0
       0                               0
Bank Sta=9899.034,10100.98
Exp/Cntr=0.3,0.1

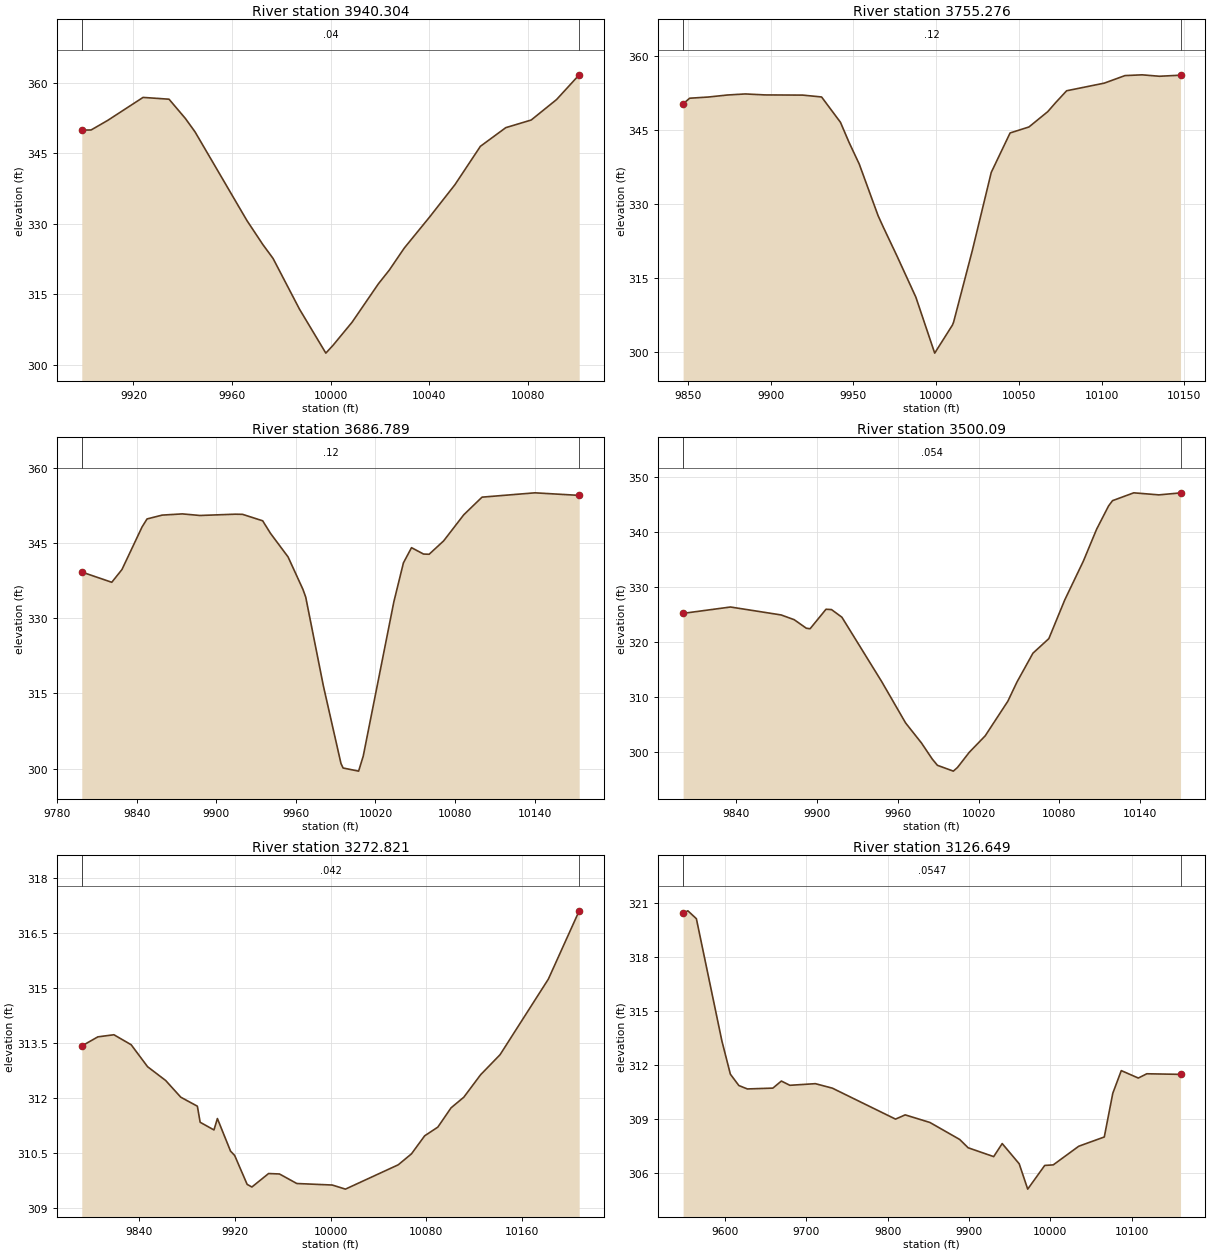
Type RM Length L Ch R = 1 ,3940.304,185.027700,185.027700,185.027700
XS GIS Cut Line= 6
678568.593647888740988.358117295678497.469489044740964.527310427
678474.161845314740955.531709156678472.313322461740954.768188847
678450.858106031740946.857532661 678376.12235295740927.877937614
#Sta/Elev= 24
9899.006349.89649902.796  349.939909.576351.98229923.889356.86089934.436356.4781
9941.053352.38919944.982349.53439966.075330.64579972.529325.54639976.664322.5983
9987.383311.81819998.102302.4398   10001304.088710008.79309.038610019.45317.1971
10023.87320.110710029.91324.769710040.23 331.40210050.55338.304810060.86346.4527
10071.18 350.425 10081.5352.049610091.82356.418210100.98361.6658
#Mann= 3 , 0 , 0
9899.006    0.04       09899.006    0.04       010100.98    0.04       0
#XS Ineff= 2 , 0
       0                               0
Bank Sta=9899.006,10100.98
Exp/Cntr=0.3,0.1

Type RM Length L Ch R = 1 ,3755.276,68.487000,68.487000,68.487000
XS GIS Cut Line= 2
678618.460380703740853.000271112678354.571491808740708.903048903
#Sta/Elev= 30
9847.037 350.3599850.979351.50179862.373351.74739873.767352.15339884.595 352.369
9896.554352.17249919.342352.13399930.736351.75559942.129346.62939947.192342.6577
9953.523 338.1339964.917327.66889968.058325.35999976.311319.52149987.704311.1916
9999.098299.843210009.79305.514210010.49306.083510021.89320.705410033.28336.4685
10044.67344.461910056.07345.675810067.46348.789510072.39350.678610078.85353.0135
10101.64354.563110114.12356.090510124.43356.244810134.98355.9534 10147.7356.1702
#Mann= 3 , 0 , 0
9847.037    0.12       09847.037    0.12       0 10147.7    0.12       0
#XS Ineff= 2 , 0
       0                               0
Bank Sta=9847.037,10147.7
Exp/Cntr=0.3,0.1

Type RM Length L Ch R = 1 ,3686.789,186.699300,186.699300,186.699300
XS GIS Cut Line= 2
678672.007983506740854.969236419678389.889927983 740607.57340309
#Sta/Elev= 30
9798.474339.22799821.095337.18349828.762339.71939843.929 348.2169847.696349.8178
9859.096350.58519874.297350.82749887.597350.50999914.198350.76719919.764 350.737
9934.931349.44999940.798346.95499954.099 342.2379965.265335.79039967.399334.2309
  9980.7 316.537    9994301.01879995.599 300.131 10007.3299.507810010.77302.4831
 10033.9333.3072 10041.1341.0549 10047.2 344.08910056.27342.8184 10060.5342.7731
10071.43345.4394 10086.6350.6447 10100.4354.1681 10140.3355.0307 10173.7354.5203
#Mann= 3 , 0 , 0
9798.474    0.12       09798.474    0.12       0 10173.7    0.12       0
#XS Ineff= 2 , 0
       0                               0
Bank Sta=9798.474,10173.7
Exp/Cntr=0.3,0.1

Type RM Length L Ch R = 1 , 3500.09,227.269000,227.269000,227.269000
XS GIS Cut Line= 2
678834.768400162740713.910208642678522.268400162740516.427569762
#Sta/Elev= 30
9800.446325.1964 9835.66326.34979873.282324.90779882.978324.04579892.001322.4939
9894.807322.39929906.636325.9424 9910.72325.88079918.466 324.4899948.158312.7324
9965.784305.27559977.613301.62059985.596298.70939989.442297.570610001.27296.5141
10004.32297.1714 10013.1299.936510024.93302.925210041.75309.214210048.59 312.729
10060.42317.953710072.25320.603910084.08327.648110097.91334.701510107.74340.4904
10116.63344.723310119.57345.685410135.35347.108810154.07346.736210170.12 347.098
#Mann= 3 , 0 , 0
9800.446   0.054       09800.446   0.054       010170.12   0.054       0
#XS Ineff= 2 , 0
       0                               0
Bank Sta=9800.446,10170.12
Exp/Cntr=0.3,0.1

Type RM Length L Ch R = 1 ,3272.821,146.171800,146.171800,146.171800
XS GIS Cut Line= 4
678953.633174151740554.659284949678852.129511356 740449.15326421
678699.039001912 740377.58094506678599.466507494740363.253034934
#Sta/Elev= 30
9791.755313.41929805.159313.66829818.631 313.7269833.055313.45379846.788312.8548
9861.902312.47979874.541312.02459888.418311.77899890.749311.34139902.294311.1322
9905.173311.44269916.171310.55419919.597310.43819930.047309.6489 9934.02309.5772
9947.967309.9441 9957.07309.93259971.579309.672610001.23 309.63110012.26309.5195
10056.42310.182610067.46310.4803 10078.5310.971710089.54311.209710100.58311.7345
10111.24312.023910125.28312.635710141.55313.181810181.96315.242110207.75317.1026
#Mann= 3 , 0 , 0
9791.755   0.042       09791.755   0.042       010207.75   0.042       0
#XS Ineff= 2 , 0
       09887.157                       0
Bank Sta=9791.755,10207.75
Exp/Cntr=0.3,0.1

Type RM Length L Ch R = 1 ,3126.649,96.226700,96.226700,96.226700
XS GIS Cut Line= 4
679103.372757465740640.596784934679038.268590838740427.055118293
678975.492890865740328.989723608678715.351924121740248.669701621
#Sta/Elev= 30
9548.258320.4559 9554.11320.57559564.564320.13879595.927313.35769606.382311.5086
9616.836310.87769627.291310.68969658.654310.73539669.108311.12749679.563310.8914
9710.926310.98229731.835310.73359809.564309.01519821.438  309.259851.759308.8309
9888.457307.88699898.923307.4242 9930.32306.93359940.786307.65829961.718306.5346
9972.183 305.1299993.115306.443910003.58306.474810034.98307.509910066.38 308.023
10076.84310.446610087.31311.707310108.24311.2941 10118.7311.5318 10160.2311.4988
#Mann= 3 , 0 , 0
9548.258  0.0547       09548.258  0.0547       0 10160.2  0.0547       0
#XS Ineff= 2 , 0
       09893.895                       0
Bank Sta=9548.258,10160.2
Exp/Cntr=0.3,0.1

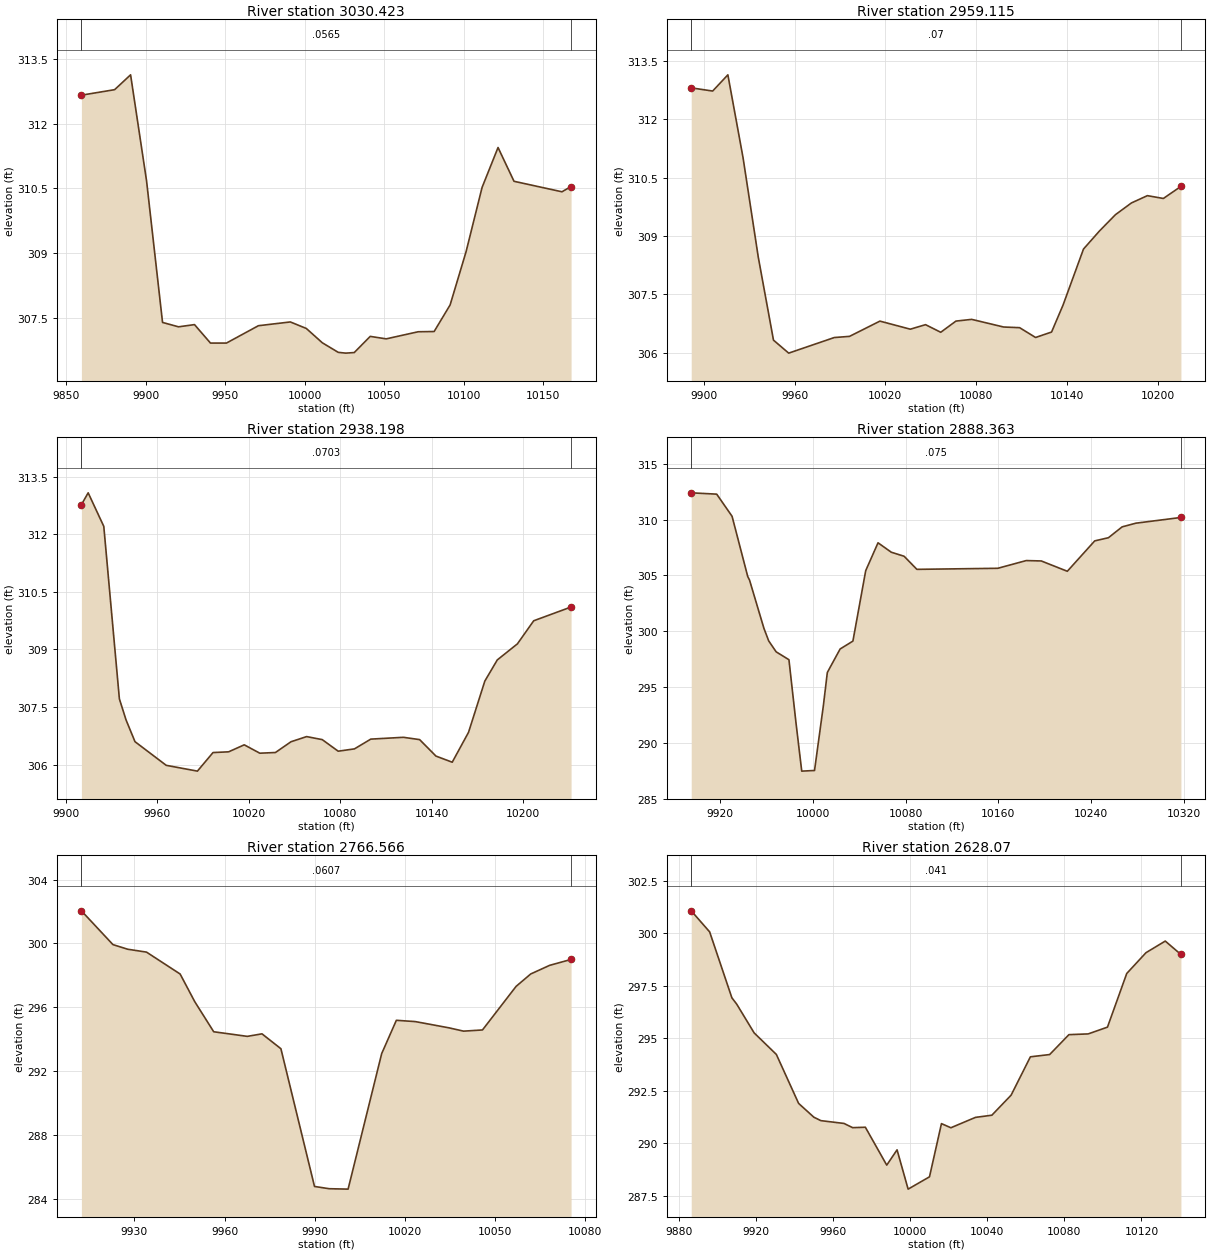
Type RM Length L Ch R = 1 ,3030.423,71.307700,71.307700,71.307700
XS GIS Cut Line= 2
 679055.79165712740197.642997935678749.268296272740229.795798033
#Sta/Elev= 27
9859.467312.65519880.372312.78229890.427313.12529900.482310.67489910.537307.4066
9920.592307.30519930.647307.35649940.702  306.939950.756  306.939970.866307.3307
9990.976307.417610001.03307.267110011.09306.936710021.14306.715310025.84306.6976
 10031.2306.711110041.25307.084210051.31307.027110071.41307.191110081.47307.1968
10091.52307.810210101.58309.041110111.63310.523310121.69311.446510131.74310.6662
10161.91 310.42410167.67310.5451
#Mann= 3 , 0 , 0
9859.467  0.0565       09859.467  0.0565       010167.67  0.0565       0
#XS Ineff= 2 , 0
       09879.418                       0
Bank Sta=9859.467,10167.67
Exp/Cntr=0.3,0.1

Type RM Length L Ch R = 1 ,2959.115,20.917200,20.917200,20.917200
XS GIS Cut Line= 3
679059.101924121740161.430118278678882.018590838740143.200951621
678743.997757465740190.075951621
#Sta/Elev= 27
 9891.63312.80469905.806312.72279915.859313.13969925.912311.00519935.965308.4524
9946.017  306.32 9956.07305.98649986.229306.38719996.282 306.41710016.39 306.809
10036.49306.601710046.55 306.718 10056.6306.522410066.65306.809510077.06 306.854
10098.18306.657510108.74306.640810119.31306.388510129.87306.528110137.44307.2187
10150.99308.661410161.55309.125910172.11309.544710182.67309.846110193.23310.0341
10203.79309.961410215.41310.2715
#Mann= 3 , 0 , 0
 9891.63    0.07       0 9891.63    0.07       010215.41    0.07       0
#XS Ineff= 2 , 0
       09894.767                       0
Bank Sta=9891.63,10215.41
Exp/Cntr=0.3,0.1

Type RM Length L Ch R = 1 ,2938.198,49.834700,49.834700,49.834700
XS GIS Cut Line= 3
679049.343481481740151.218617693678889.621259302740116.496395484
678742.051814824740172.051951036
#Sta/Elev= 29
9910.257312.77039914.702313.07949924.936312.20639935.169307.71189939.531307.1653
9945.403306.5979 9965.87305.98219986.337305.83099996.571306.3146 10006.8306.3336
10017.04306.515710027.27306.297710037.51306.315910047.74306.596710057.97306.7304
10068.21306.651110078.65306.350310089.33306.410510100.02306.664510121.39306.7117
10132.07306.651610142.76306.222810153.44306.063210164.13306.841710174.81308.1756
10182.99308.727410196.18309.145610206.87 309.74710231.39310.1057
#Mann= 3 , 0 , 0
9910.257  0.0703       09910.257  0.0703       010231.39  0.0703       0
#XS Ineff= 2 , 0
       0                               0
Bank Sta=9910.257,10231.39
Exp/Cntr=0.3,0.1

Type RM Length L Ch R = 1 ,2888.363,121.796900,121.796900,121.796900
XS GIS Cut Line= 4
679071.434835225740148.414278388679024.559835225740106.747611701
678902.164001852 740049.45594503678712.059835225740169.247611716
#Sta/Elev= 30
9894.983312.39259916.972312.27399930.226310.29199943.731304.90629945.278304.5871
  9957.7 300.2679961.822299.13979968.255298.15969979.296297.4525 9985.41291.7775
9990.338287.479910001.38 287.537   10009293.334610012.42296.309910023.46298.4127
 10034.5299.119510045.54 305.42410056.17307.918710067.63 307.07510078.67306.7147
10089.71305.542110159.51305.637110184.05306.327610197.03306.293810219.51305.3702
10243.15308.089810254.97308.373110266.79309.344210278.61309.674210317.54 310.187
#Mann= 3 , 0 , 0
9894.983   0.075       09894.983   0.075       010317.54   0.075       0
#XS Ineff= 2 , 0
       09903.104                       0
Bank Sta=9894.983,10317.54
Exp/Cntr=0.3,0.1

Type RM Length L Ch R = 1 ,2766.566,138.495700,138.495700,138.495700
XS GIS Cut Line= 2
679124.384297341740021.874357447678978.624936938739948.994677216
#Sta/Elev= 23
9912.377 302.0439922.869299.92799927.749 299.6399934.049299.4562 9945.23298.0861
9950.109296.3508 9956.41294.46849967.591  294.18 9972.47294.33829978.771293.4062
9989.951284.77959994.831284.638110001.13284.612110012.31293.102610017.19295.1859
10023.49295.105510034.67294.715710039.55294.506810045.85294.581210057.03297.3101
10061.91298.088810068.21298.629110075.34298.9986
#Mann= 3 , 0 , 0
9912.377  0.0607       09912.377  0.0607       010075.34  0.0607       0
#XS Ineff= 2 , 0
       0                               0
Bank Sta=9912.377,10075.34
Exp/Cntr=0.3,0.1

Type RM Length L Ch R = 1 , 2628.07,59.293900,59.293900,59.293900
XS GIS Cut Line= 4
679186.812511086739943.281079829679149.909716636739879.316236079
679083.484686553739847.333814204678976.876613647739844.873627901
#Sta/Elev= 30
9886.264301.06559895.824 300.0649907.369296.92539909.902296.62139918.914295.2576
9930.459294.23089942.004291.90159949.924291.24419953.548291.08099965.559290.9472
 9970.06290.74659976.658290.76659987.757288.96299993.111289.69099998.856287.8213
10009.95288.406910016.16290.938310021.05290.741610033.83291.236310042.32291.3383
10052.32292.293510062.33294.118110072.33294.226110082.33295.172810092.33295.2079
10102.34295.530510112.34298.083510122.34299.073810132.34 299.62610140.47298.9886
#Mann= 3 , 0 , 0
9886.264   0.041       09886.264   0.041       010140.47   0.041       0
#XS Ineff= 2 , 0
       0                               0
Bank Sta=9886.264,10140.47
Exp/Cntr=0.3,0.1

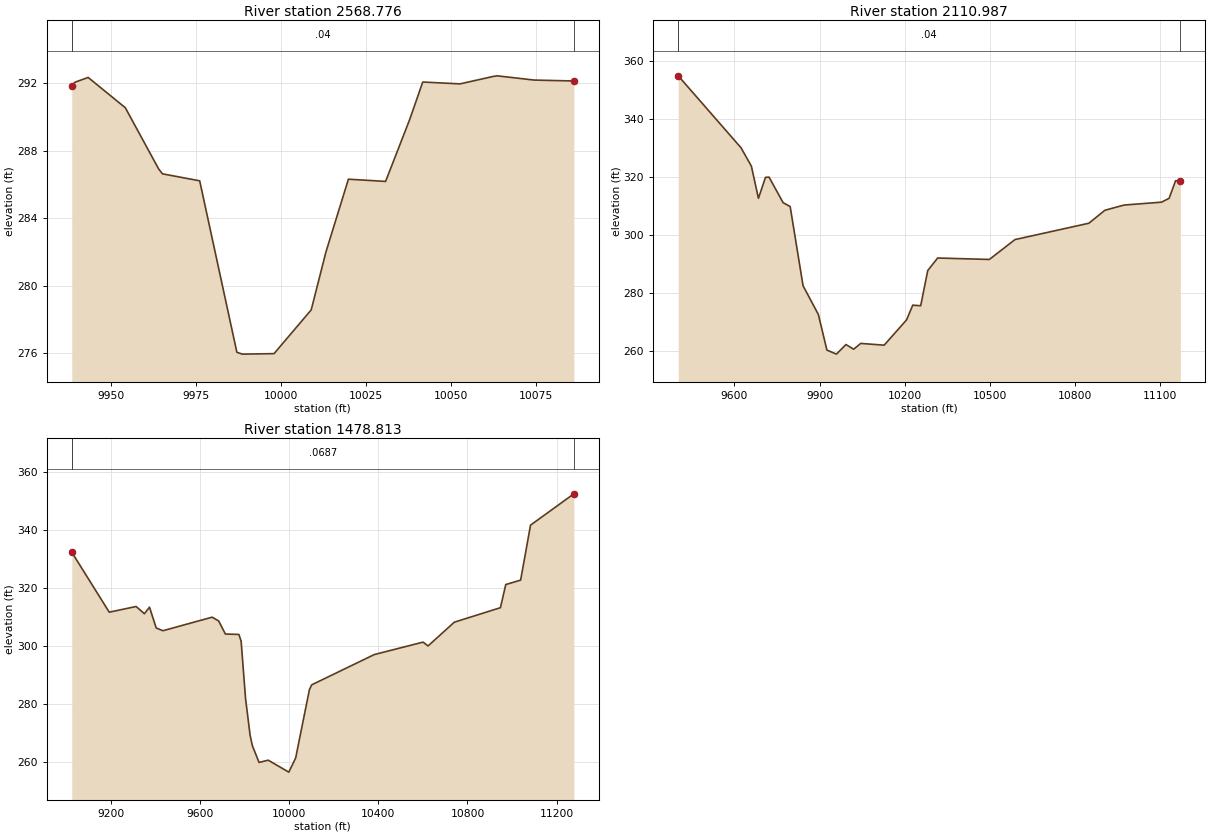
Type RM Length L Ch R = 1 ,2568.776,457.789700,457.789700,457.789700
XS GIS Cut Line= 2
679199.407497585739835.388116896 679064.36573717739775.369556725
#Sta/Elev= 22
9938.342291.87649939.297292.07269943.165292.35329954.108290.55819963.919286.9303
9965.051286.64249975.994286.22969986.937276.07119988.541275.96039997.881275.9892
10008.82278.583110013.16282.018410019.77286.325510030.71286.192610037.79289.8521
10041.65292.0826 10052.6291.972710062.41 292.41410063.54292.450110074.48 292.198
10085.43292.148310086.12292.1279
#Mann= 3 , 0 , 0
9938.342    0.04       09938.342    0.04       010086.12    0.04       0
#XS Ineff= 2 , 0
       0                               0
Bank Sta=9938.342,10086.12
Exp/Cntr=0.3,0.1

Type RM Length L Ch R = 1 ,2110.987,632.173500,632.173500,632.173500
XS GIS Cut Line= 3
679722.355205715 739023.37201418679006.209372401 739552.88590309
678593.882983506740329.795625314
#Sta/Elev= 30
 9401.64354.78119623.039329.9755 9659.52323.64519684.394312.54349709.267319.7662
9721.704319.8668 9771.45311.04519796.324309.7063  9841.7282.40359895.817272.4618
  9925.8260.2204 9959.44258.8208 9993.08262.131110020.18260.513610045.06262.5135
10127.64261.909110206.73270.634410228.56275.708910256.48275.502610281.35287.6314
 10316.2291.963510498.46291.462710589.03298.316310849.41303.953410906.02308.4311
10973.94310.227311105.46311.213211132.44312.556911155.08318.599211171.83318.6096
#Mann= 3 , 0 , 0
 9401.64    0.04       0 9401.64    0.04       011171.83    0.04       0
#XS Ineff= 2 , 0
       0                               0
Bank Sta=9401.64,11171.83
Exp/Cntr=0.3,0.1

Type RM Length L Ch R = 1 ,1478.813,122.208800,122.208800,122.208800
XS GIS Cut Line= 6
678793.738727182738511.486054286678657.110064954738600.627925366
678576.554509461738742.294592053678609.887842774739253.405703157
678757.432989746739810.185323045678431.205861032740579.754538581
#Sta/Elev= 30
9024.465332.37969192.631311.64169313.254313.6082 9350.57311.10519373.284313.3796
9403.295306.19459433.307305.22579654.404309.91279683.605308.6135 9713.82 304.087
 9774.25303.95259784.322301.69989804.466281.66329824.609269.15289834.681265.5418
9864.927 259.7029906.002260.48129998.419256.350610029.23261.251110090.84284.8666
10101.11286.524210381.89296.987810601.01301.296710623.19299.969810741.01 308.179
10948.05313.197610971.87321.193711038.59322.721411083.07341.726711277.41352.5549
#Mann= 3 , 0 , 0
9024.465  0.0687       09024.465  0.0687       011277.41  0.0687       0
#XS Ineff= 2 , 0
       0                               0
Bank Sta=9024.465,11277.41
Exp/Cntr=0.3,0.1