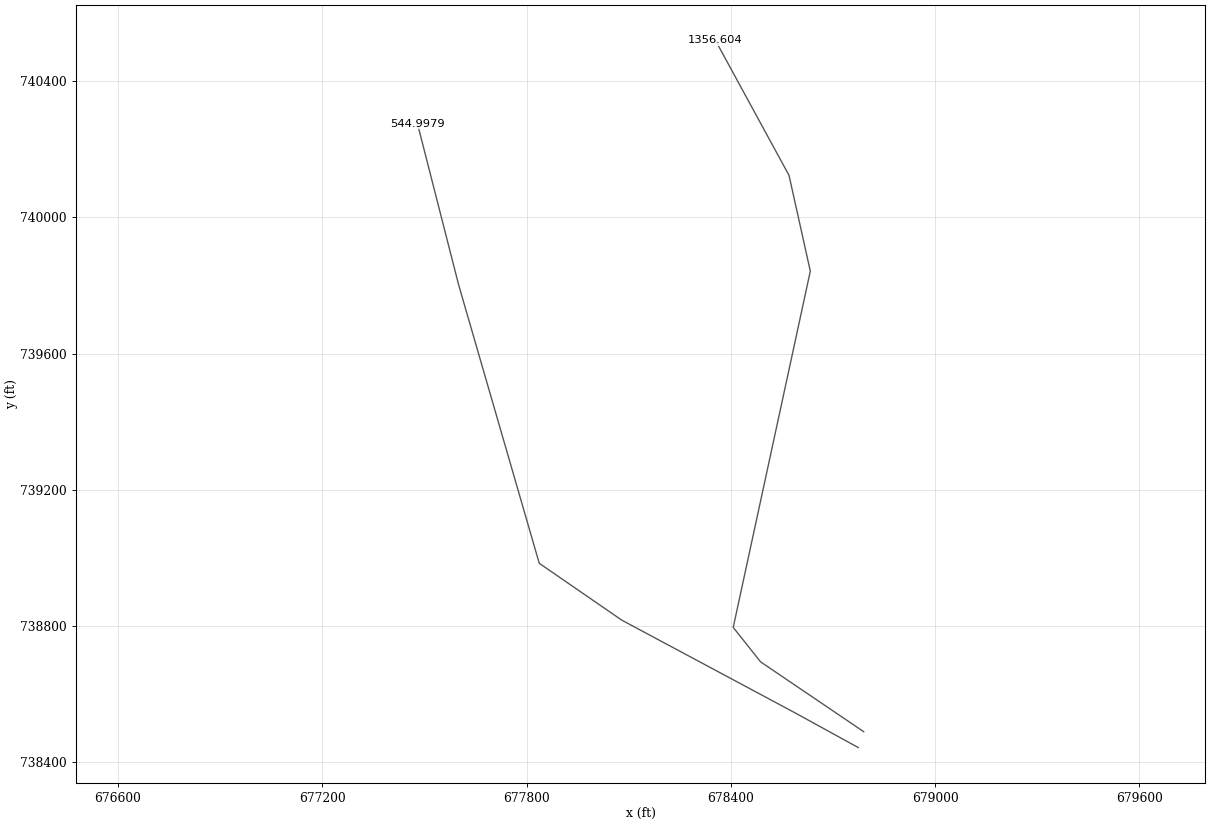
HEC-RAS study 4010_ras.prj: 4010

--- 4010_ras.g01 (geometry) --- (continued)

Type RM Length L Ch R = 3 , 1424.55,,,
BEGIN DESCRIPTION:
END DESCRIPTION:
Bridge Culvert--1,0,-1,-1, 0
Deck Dist Width WeirC Skew NumUp NumDn MinLoCord MaxHiCord MaxSubmerge Is_Ogee
34.201550,53.805700,2.6,0, 60, 60, , , 0.95, 0, 0,0,,
 9322.45 9387.29 9490.97 9508.60 9535.17 9559.57 9569.85 9610.99 9641.84 9662.41
 9691.37 9713.84 9734.41 9771.45 9784.47 9784.4710095.8310095.8310135.5110175.80
10185.8310236.0110276.1610286.2010306.2710326.3410336.3810346.6310367.2410377.54
10387.8510398.1510408.4510418.7610439.3610459.9710470.1110500.1210520.1310540.13
10550.1410570.1410580.1410590.1510600.1510610.1510620.1610630.1610640.2410664.65
10686.0510701.2710713.4810720.9210725.6810750.1010755.8010773.2410790.6810792.39
  305.46  303.76  300.44  299.96  299.40  298.44  298.16  296.73  296.07  295.51
  295.01  294.45  294.24  293.41  293.29  293.29  290.35  290.35  290.01  289.95
  289.83  290.12  290.73  291.01  291.93  292.58  292.34  292.50  293.48  294.66
  295.37  295.94  295.88  296.40  297.00  297.09  297.80  298.11  297.91  298.07
  298.63  299.00  300.43  301.44  302.22  302.23  302.42  303.57  304.23  305.04
  305.95  306.44  306.30  306.47  306.39  305.54  305.66  306.68  307.53  307.70
 -694.54 -696.24 -699.56 -700.04 -700.60 -701.56 -701.84 -703.27 -703.93 -704.49
 -704.99 -705.55 -705.76 -706.59 -706.71  286.79  283.85 -709.65 -709.99 -710.05
 -710.17 -709.88 -709.27 -708.99 -708.07 -707.42 -707.66 -707.50 -706.52 -705.34
 -704.63 -704.06 -704.12 -703.60 -703.00 -702.91 -702.20 -701.89 -702.09 -701.93
 -701.37 -701.00 -699.57 -698.56 -697.78 -697.77 -697.58 -696.43 -695.77 -694.96
 -694.05 -693.56 -693.70 -693.53 -693.61 -694.46 -694.34 -693.32 -692.47 -692.30
 9322.45 9387.29 9490.97 9508.60 9535.17 9559.57 9569.85 9610.99 9641.84 9662.41
 9691.37 9713.84 9734.41 9771.45 9779.53 9779.5310090.8810090.8810135.5110175.80
10185.8310236.0110276.1610286.2010306.2710326.3410336.3810346.6310367.2410377.54
10387.8510398.1510408.4510418.7610439.3610459.9710470.1110500.1210520.1310540.13
10550.1410570.1410580.1410590.1510600.1510610.1510620.1610630.1610640.2410664.65
10686.0510701.2710713.4810720.9210725.6810750.1010755.8010773.2410790.6810792.39
  305.46  303.76  300.44  299.96  299.40  298.44  298.16  296.73  296.07  295.51
  295.01  294.45  294.24  293.41  293.34  293.34  290.39  290.39  290.01  289.95
  289.83  290.12  290.73  291.01  291.93  292.58  292.34  292.50  293.48  294.66
  295.37  295.94  295.88  296.40  297.00  297.09  297.80  298.11  297.91  298.07
  298.63  299.00  300.43  301.44  302.22  302.23  302.42  303.57  304.23  305.04
  305.95  306.44  306.30  306.47  306.39  305.54  305.66  306.68  307.53  307.70
 -694.54 -696.24 -699.56 -700.04 -700.60 -701.56 -701.84 -703.27 -703.93 -704.49
 -704.99 -705.55 -705.76 -706.59 -706.66  286.84  283.89 -709.61 -709.99 -710.05
 -710.17 -709.88 -709.27 -708.99 -708.07 -707.42 -707.66 -707.50 -706.52 -705.34
 -704.63 -704.06 -704.12 -703.60 -703.00 -702.91 -702.20 -701.89 -702.09 -701.93
 -701.37 -701.00 -699.57 -698.56 -697.78 -697.77 -697.58 -696.43 -695.77 -694.96
 -694.05 -693.56 -693.70 -693.53 -693.61 -694.46 -694.34 -693.32 -692.47 -692.30
Pier Skew, UpSta & Num, DnSta & Num=  ,9887.59, 2 ,9882.64, 2 , 0 , 0 , 0 ,,
    4.00    4.00
 -707.68  292.32
    4.00    4.00
 -707.64  292.36
Pier Skew, UpSta & Num, DnSta & Num=  ,9992.71, 2 ,9987.76, 2 , 0 , 0 , 0 ,,
    4.00    4.00
 -708.68  291.32
    4.00    4.00
 -708.63  291.37
BR Coef=-1 , 0 , 0 ,, 0 ,,,0.8,0,1,0,
WSPro=,,,, 1 ,,,, 0 ,,,, 0 ,,,,-1 ,-1 ,-1 , 0 , 0 , 0 , 0 , 0
BC Design=,, 0 ,, 0 ,,,,,,

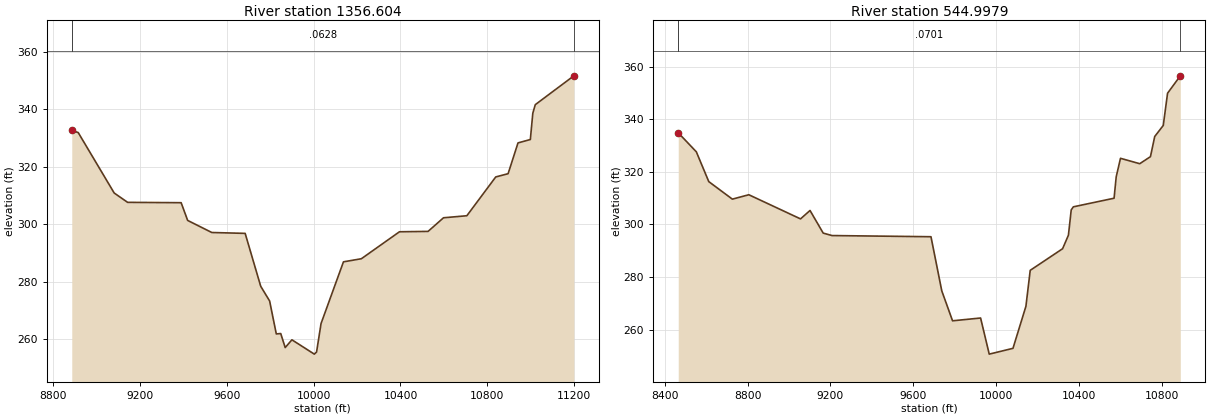
Type RM Length L Ch R = 1 ,1356.604,811.606500,811.606500,811.606500
XS GIS Cut Line= 6
678790.064620405738489.686353967678487.144787252738694.829314262
678406.936453909738795.870980933678633.325342804739842.120980933
678570.825342745740123.370980933678354.048942387740521.066031292
#Sta/Elev= 30
8884.723  332.648914.414331.87899080.397310.82569142.183307.58139388.896307.4587
9418.942301.28869530.257 297.0829684.018296.77659755.773278.35649796.775273.2488
9827.528261.77179848.029261.89619868.575257.01599899.559259.721410002.84254.7348
10013.17 255.46510033.82265.3699 10137.1286.868510219.72287.9459 10395.3297.3333
10527.21297.468310598.38302.209210705.97  302.9210839.19316.428210896.13317.5566
10941.69328.274410998.64329.456811010.03338.627711021.41341.594811199.16351.6337
#Mann= 3 , 0 , 0
8884.723  0.0628       08884.723  0.0628       011199.16  0.0628       0
#XS Ineff= 2 , 0
       0                               0
Bank Sta=8884.723,11199.16
Exp/Cntr=0.3,0.1

Type RM Length L Ch R = 1 ,544.9979,0.000000,0.000000,0.000000
XS GIS Cut Line= 6
678774.176689029738442.981913283678590.781941056738543.719711483
678079.533960164738817.282227546677837.271340013738984.174254805
677600.392333537739802.483549684677479.798542947740274.638899446
#Sta/Elev= 30
8465.609334.82248552.884327.58488612.991316.24598726.774309.58058806.165311.2532
9055.681302.06819101.479305.27089165.067296.66749207.458295.73349685.068295.2874
9737.121274.72349789.173263.3137 9924.51264.37939966.153250.642610080.67252.8447
10143.13268.827210163.95282.509110320.11290.724610348.24295.875910361.75305.4891
10372.16306.660210568.51309.931910578.83318.090410599.47325.110610692.36323.0591
10743.97325.733110764.61333.395210805.89337.611110826.53349.850310888.09356.4765
#Mann= 3 , 0 , 0
8465.609  0.0701       08465.609  0.0701       010888.09  0.0701       0
#XS Ineff= 2 , 0
       0                               0
Bank Sta=8465.609,10888.09
Exp/Cntr=0.3,0.1